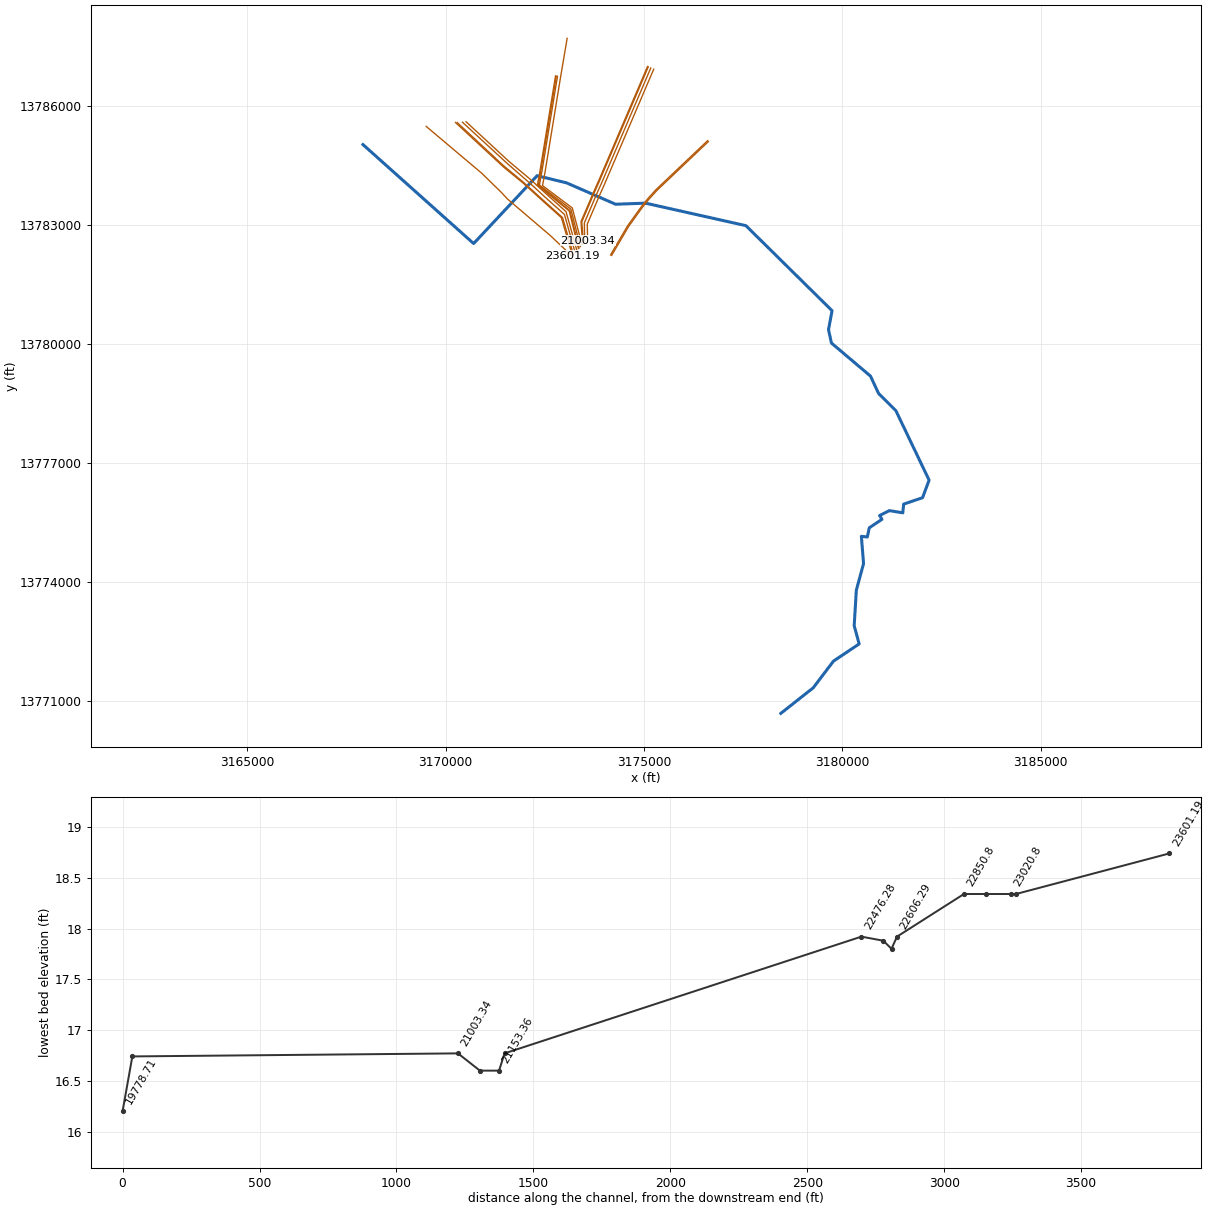
--- A119-00-00.prj (project) ---

Proj Title=A119-00-00
Current Plan=p02
Default Exp/Contr=.3,.1
English Units
Geom File=g01
Flow File=f01
Flow File=f02
Plan File=p01
Plan File=p02
Y Axis Title=Elevation
X Axis Title(PF)=Main Channel Distance
X Axis Title(XS)=Station
BEGIN DESCRIPTION:
Clear Creek
Turkey Creek
HCFCD Unit A119-00-00
Flood Hazard Model
10, 2, 1, 0.2% Event
Filename A119_00_00.prj
Prepared by: Matthew Fischer Date: 2-20-04
Reviewd by:		Date:
Status Final Submittal
Updated by LOMR 18-06-2511P
END DESCRIPTION:
DSS File=dss
DSS Export Rating Curves= 0
DSS Export Rating Curve Sorted= 0
DSS Export Volume Flow Curves= 0
DXF OffsetX= 0
DXF OffsetY= 0
DXF ScaleX= 1
DXF ScaleY= 10

--- A119-00-00.p02 (plan) ---

Plan Title=Effective Floodway 2018
Program Version=3.0.1
Short Identifier=Eff+LOMR FW
Geom File=g01
Flow File=f02
Subcritical Flow
K Sum by GR= 0
Std Step Tol= 0.01
Critical Tol= 0.01
Num of Std Step Trials= 20
Max Error Tol= 0.3
Flow Tol Ratio= 0.001
Split Flow NTrial= 30
Split Flow Tol= 0.02
Split Flow Ratio= 0.02
Log Output Level= 0
Friction Slope Method= 0
Unsteady Friction Slope Method= 2
Unsteady Bridges Friction Slope Method= 1
Secant Critical Depth
Global Vel Dist= 0 , 0 , 0
Global Log Level= 0
CheckData=True
Encroach Param=-1 ,0,0, 2
Encroach River=A119-00-00
Encroach Reach=A119-00-00_0002
Encroach Node=23601.19
       1 4969.92 5030.08
Encroach Node=23040.8
       1 4969.38 5030.62
Encroach Node=23020.8
       1 4969.92 5030.08
Encroach Node=22975
       1    4700    5300
Encroach Node=22930.8
       1 4969.92 5030.08
Encroach Node=22850.8
       1 4969.38 5030.62
Encroach Node=22606.29
       1 4968.77 5031.23
Encroach Node=22586.28
       1 4968.77 5031.23
Encroach Node=22571
       1    4700    5300
Encroach Node=22556.28
       1    4900    5100
Encroach Node=22476.28
       1    4900    5100
Encroach Node=21173.36
       1 4966.32 5033.68
Encroach Node=21153.36
       1 4966.32 5033.68
Encroach Node=21118
       1    4600    5400
Encroach Node=21083.36
       1 4966.32 5033.68
Encroach Node=21003.34
       1 4966.32 5033.68
Encroach Node=19814.41
       1 4933.55 5066.45
Encroach Node=19778.71
       1 4933.55 5066.45
Encroach Node=19695
       1    4800    5200
Encroach Node=19612.32
       1 4933.55 5066.45
Encroach Node=19483.95
       1 4933.55  5062.4
Encroach Node=19345.9
       1  4957.5  5042.5
Encroach Node=17856.15
       1 4956.82    5600
Encroach Node=17836.1
       1 4956.82    5600
Encroach Node=17791
       1    4700    5600
Encroach Node=17746
       1 4956.82    5600
Encroach Node=17666
       1 4956.82    5600
Encroach Node=16761.5
       1    4800    5200
Encroach Node=16538
       1    4961    5155
Encroach Node=16342.12
       1    4961    5155
Encroach Node=16161.62
       1    4800    5200
Encroach Node=16142.95
       1    4800    5200
Encroach Node=16081
       1    4800    5200
Encroach Node=16021.58
       1 4934.41    5200
Encroach Node=15941.54
       1 4925.74    5200
Encroach Node=15608.93
       1 4929.52 5055.45
Encroach Node=15011.6
       1  4942.6 5070.45
Encroach Node=14915.01
       1  4927.6 5070.45
Encroach Node=13691.93
       1 4952.11    5150
Encroach Node=13671.31
       1 4952.11    5150
Encroach Node=13635
       1 4952.11    5150
Encroach Node=13599.62
       1 4952.11    5150
Encroach Node=13518.95
       1 4952.11    5150
Encroach Node=13018.9
       1 4901.38 5469.38
Encroach Node=12968.9
       1 4900.79 5505.79
Encroach Node=12861.99
       1 4918.69    5600
Encroach Node=12841.5
       1 4923.69    5600
Encroach Node=12780
       1 4918.69    5600
Encroach Node=12719.49
       1 4918.69    5600
Encroach Node=12639.46
       1 4918.69    5600
Encroach Node=12148.93
       1 4911.11    5600
Encroach Node=12140
       1 4915.77    5600
Encroach Node=12133.92
       1 4915.77    5600
Encroach Node=11277.35
       1    4750    5600
Encroach Node=11267.35
       1    4750    5600
Encroach Node=11242
       1    4750    5600
Encroach Node=11217.32
       1    4750    5600
Encroach Node=11177.08
       1    4750    5600
Encroach Node=9853.579
       1    4600    5600
Encroach Node=9843
       1    4600    5600
Encroach Node=9832.981
       1    4600    5600
Encroach Node=8541.402
       1    4600    5400
Encroach Node=8520.751
       1    4700    5300
Encroach Node=8500
       1    4700    5300
Encroach Node=8479.856
       1    4900    5100
Encroach Node=8365.985
       1    4900    5100
Encroach Node=8358
       1    4800    5200
Encroach Node=8350.878
       1    4800    5200
Encroach Node=6246.868
       1    4800    5200
Encroach Node=5032.265
       1    4900    5100
Encroach Node=4343.861
       1 4917.76 5038.37
Encroach Node=3908.342
       1 4931.71 5117.74
Encroach Node=3672.959
       1 4872.64 5074.88
Encroach Node=2924.523
       1 4856.44 5059.51
Encroach Node=2477.631
       1 4956.28 5043.72
Encroach Node=2472
       1 4956.28 5043.72
Encroach Node=2467.477
       1 4956.28 5043.72
Encroach Node=2411.204
       1 4947.11 5052.89
Encroach Node=2390.318
       1 4947.11 5052.89
Encroach Node=2365
       1 4947.11 5052.89
Encroach Node=2339.021
       1 4947.11 5052.89
Encroach Node=2258.236
       1 4947.11 5052.89
Encroach Node=390.146
       1  4976.8  5053.2
Encroach Node=370.056
       1  4961.8  5038.2
Encroach Node=339
       1  4961.8  5048.2
Encroach Node=308.336
       1  4971.8  5048.2
Encroach Node=196.239
       1 4972.68 5087.32
BEGIN DESCRIPTION:
FEMA Effective 2007 + LOMR 08-06-2049P+ LOMR 18-06-2511P
END DESCRIPTION:
Computation Interval=1HOUR
Output Interval=1HOUR
Instantaneous Interval=1HOUR
Mapping Interval=1HOUR
Run HTab= 0
Run UNet= 0
Run Sediment= 0
Run PostProcess= 0
Run WQNet= 0
Run RASMapper= 0
UNET Theta= 1
UNET Theta Warmup= 1
UNET ZTol= 0.02
UNET ZSATol= 0.1
UNET MxIter= 20
UNET Max Iter WO Improvement= 0
UNET MaxInSteps= 20
UNET DtIC= 0
UNET DtMin= 0
UNET MaxCRTS= 20
UNET WFStab= 2
UNET SFStab= 1
UNET WFX= 1
UNET SFX= 1
UNET DSS MLevel= 4
UNET Pardiso=0
UNET DZMax Abort= 100
UNET Use Existing IB Tables=-1
UNET Froude Reduction=False
UNET Froude Limit= 0.8
UNET Froude Power= 4
UNET Time Slicing=0,0, 5
UNET Junction Losses=0
UNET D1 Cores= 0
UNET D2 Coriolis=0
UNET D2 Cores= 0
UNET D2 Theta= 1
UNET D2 Theta Warmup= 1
UNET D2 Z Tol= 0.01
UNET D2 Volume Tol= 0.01
UNET D2 Max Iterations= 20
UNET D2 Equation= 0
UNET D2 RampUpFraction=0.1
UNET D2 TimeSlices= 1
UNET D2 BCVolumeCheck=0
UNET D1D2 MaxIter= 0
UNET D1D2 ZTol=0.01
UNET D1D2 QTol=0.1
UNET D1D2 MinQTol=1
Write IC File= 0
Write IC File at Fixed DateTime=0
IC Time=0,,
Write IC File at Sim End=0
Echo Input=False
Echo Parameters=False
Echo Output=False
Write Detailed= 0
HDF Write Warmup=0
HDF Write Time Slices=0
HDF Flush=0
HDF Face Node Velocities=0
HDF Compression= 1
HDF Chunk Size= 1
HDF Spatial Parts= 1
HDF Use Max Rows=0
HDF Fixed Rows= 1
Calibration Method= 0
Calibration Iterations= 20
Calibration Max Change=0.05
Calibration Tolerance=0.2
Calibration Maximum=1.5
Calibration Minimum=0.5
Calibration Optimization Method= 1
WQ AD Non Conservative
WQ ULTIMATE=-1
WQ Max Comp Step=1HOUR
WQ Output Interval=15MIN
WQ Output Selected Increments= 0
WQ Output face flow=0
WQ Output face velocity=0
WQ Output face area=0
WQ Output face dispersion=0
WQ Output cell volume=0
WQ Output cell surface area=0
WQ Output cell continuity=0
WQ Output cumulative cell continuity=0
WQ Output face conc=0
WQ Output face dconc_dx=0
WQ Output face courant=0
WQ Output face peclet=0
WQ Output face adv mass=0
WQ Output face disp mass=0
WQ Output cell mass=0
WQ Output cell source sink temp=0
WQ Output nsm pathways=0
WQ Output nsm derived pathways=0
WQ Output MaxMinRange=-1
WQ Daily Max Min Mean=-1
WQ Daily Range=0
WQ Daily Time=0
WQ Create Restart=0
WQ Fixed Restart=0
WQ System Summary=0
WQ Write To DSS=0
WQ Use Fixed Temperature=0
Sorting and Armoring Iterations= 10
XS Update Threshold= 0.02
Bed Roughness Predictor= 0
Hydraulics Update Threshold= 0.02
Energy Slope Method= 1
Volume Change Method= 1
Sediment Retention Method= 0
XS Weighting Method= 0
Number of US Weighted Cross Sections= 1
Number of DS Weighted Cross Sections= 1
Upstream XS Weight=0
Main XS Weight=1
Downstream XS Weight=0
Number of DS XS's Weighted with US Boundary= 1
Upstream Boundary Weight= 1
Weight of XSs Associated with US Boundary= 0
Number of US XS's Weighted with DS Boundary= 1
Downstream Boundary Weight= 0.5
Weight of XSs Associated with DS Boundary= 0.5
Percentile Method= 0
Sediment Output Level= 4
Mass or Volume Output= 0
Output Increment Type= 1
Profile and TS Output Increment= 1
XS Output Flag= 0
XS Output Increment= 10
Write Gradation File= 0
Read Gradation Hotstart= 0
Write HDF5 File= 1
Write DSS Sediment File= 0
SV Curve= 0
Specific Gage Flag= 0

--- A119-00-00.p01 (plan) ---

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Plan Title=Effective Multi-Profile 2018
Short Identifier=Eff+LOMR MP
Geom File=g01
Flow File=f01
Encroach Param=-1 ,0,0, 0

--- A119-00-00.f02 (steady flow) ---

Flow Title=Effective Floodway 2007
Version=Version 3.0.1  May 2012
Number of Profiles= 2
Profile Names=1PCT_100yr, 1PCTFloodway_100yrFW
River Rch & RM=A119-00-00,A119-00-00_0002 ,23601.19
    1316    1316
River Rch & RM=A119-00-00,A119-00-00_0002 ,23040.8
    1352    1352
River Rch & RM=A119-00-00,A119-00-00_0002 ,22476.28
    1439    1439
River Rch & RM=A119-00-00,A119-00-00_0002 ,21173.36
    1451    1451
River Rch & RM=A119-00-00,A119-00-00_0002 ,21003.34
    3074    3074
River Rch & RM=A119-00-00,A119-00-00_0002 ,19814.41
    3510    3510
River Rch & RM=A119-00-00,A119-00-00_0002 ,14915.01
    5035    5035
River Rch & RM=A119-00-00,A119-00-00_0002 ,13691.93
    5132    5132
River Rch & RM=A119-00-00,A119-00-00_0002 ,9832.981
    5256    5256
River Rch & RM=A119-00-00,A119-00-00_0002 ,5032.265
    5328    5328
River Rch & RM=A119-00-00,A119-00-00_0002 ,2258.236
    5677    5677
River Rch & RM=A119-00-00,A119-00-00_0002 ,390.146
    5714    5714
Boundary for River Rch & Prof#=A119-00-00,A119-00-00_0002 , 1
Up Type= 0
Dn Type= 3
Dn Slope=.003
Boundary for River Rch & Prof#=A119-00-00,A119-00-00_0002 , 2
Up Type= 0
Dn Type= 3
Dn Slope=.003
DSS Import GetInterval= 0
DSS Import GetPeak= 0
DSS Import FillOption= 0

--- A119-00-00.f01 (steady flow) ---

Flow Title=Effective Multi-Profile 2007
Version=Version 3.0.1  Mar 2001
Number of Profiles= 4
Profile Names=10PCT_10yr, 2PCT_50yr, 1PCT_100yr, 0.2PCT_500yr
River Rch & RM=A119-00-00,A119-00-00_0002      ,23601.19
     663    1095    1316    2293
River Rch & RM=A119-00-00,A119-00-00_0002      ,23040.8
     690    1134    1352    2304
River Rch & RM=A119-00-00,A119-00-00_0002      ,22476.28
     759    1230    1439    2331
River Rch & RM=A119-00-00,A119-00-00_0002      ,21173.36
     768    1243    1451    2334
River Rch & RM=A119-00-00,A119-00-00_0002      ,21003.34
    1709    2643    3074    4401
River Rch & RM=A119-00-00,A119-00-00_0002      ,19814.41
    2229    3081    3510    4640
River Rch & RM=A119-00-00,A119-00-00_0002      ,14915.01
    3099    4464    5035    6321
River Rch & RM=A119-00-00,A119-00-00_0002      ,13691.93
    3176    4569    5132    6636
River Rch & RM=A119-00-00,A119-00-00_0002      ,9832.981
    3275    4704    5256    7050
River Rch & RM=A119-00-00,A119-00-00_0002      ,5032.265
    3333    4784    5328    7301
River Rch & RM=A119-00-00,A119-00-00_0002      ,2258.236
    3508    5086    5677    7904
River Rch & RM=A119-00-00,A119-00-00_0002      ,390.146
    3526    5118    5714    7969
Boundary for River Rch & Prof#=A119-00-00,A119-00-00_0002      , 1
Up Type= 0
Dn Type= 3
Dn Slope=.003
Boundary for River Rch & Prof#=A119-00-00,A119-00-00_0002      , 2
Up Type= 0
Dn Type= 3
Dn Slope=.003
Boundary for River Rch & Prof#=A119-00-00,A119-00-00_0002      , 3
Up Type= 0
Dn Type= 3
Dn Slope=.003
Boundary for River Rch & Prof#=A119-00-00,A119-00-00_0002      , 4
Up Type= 0
Dn Type= 3
Dn Slope=.003
DSS Import GetInterval= 0
DSS Import GetPeak= 0
DSS Import FillOption= 0

--- A119-00-00.g01 (geometry) ---

Geom Title=A119-00-00 2018
Program Version=3.0.1

River Reach=A119-00-00      ,A119-00-00_0002
Reach XY= 30
       3167918.5       13785027.       3170707.5    13782532.999
       3172307.5       13784243.      3173049.75       13784062.
      3174284.25       13783524.        3175039.       13783551.
      3177568.75       13782984.        3179740.    13780841.001
      3179649.75       13780366.        3179724.       13780026.
        3180708.    13779193.001       3180912.5       13778754.
      3181347.75       13778322.       3182184.5       13776572.
        3182020.    13776129.001        3181543.       13775967.
       3181522.5       13775748.        3181182.       13775803.
      3180937.75       13775679.       3180996.5       13775584.
        3180678.       13775370.      3180627.25       13775138.
      3180478.25       13775156.        3180533.       13774467.
      3180351.25       13773799.      3180297.25       13772904.
       3180422.5    13772443.999       3179774.5       13772010.
     3179265.473    13771338.803     3178448.712       13770694.

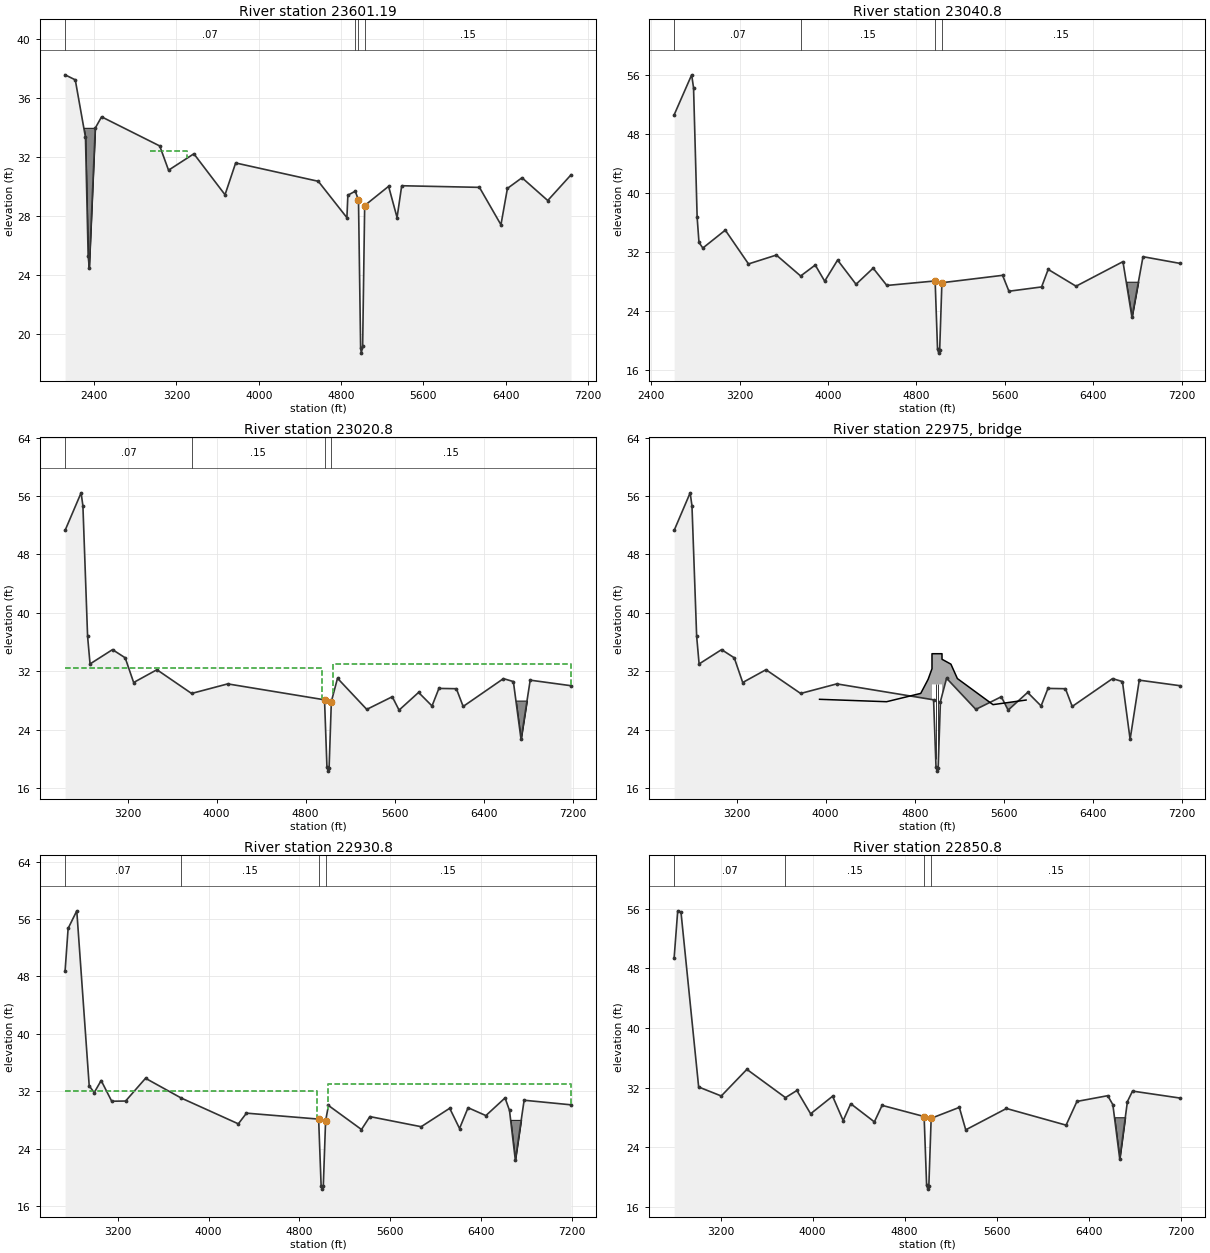
Type RM Length L Ch R = 1 ,23601.19,567.11,560.39,552.23
XS GIS Cut Line= 6
      3169512.41    13785484.963     3170911.663    13784305.375
     3171409.293    13783818.856     3171559.638    13783656.078
     3172642.054    13782732.669     3173185.654    13782218.536
#Sta/Elev= 30
 2117.06   37.56 2216.07   37.22 2315.16   33.34 2341.27   25.34 2351.98   24.53
 2410.53   33.96 2471.96   34.72 3037.27   32.75 3122.98   31.11 3369.18   32.22
 3672.17   29.45  3775.6    31.6 4579.03   30.36 4857.31    27.9 4866.62   29.42
 4938.43   29.69 4969.92   29.09 4990.59   19.12 4997.23   18.74 5010.36   19.21
 5030.08   28.72 5262.67   30.02 5344.95   27.91 5390.13   30.06 6145.96   29.95
 6355.11   27.42 6418.03   29.88 6559.85    30.6  6810.1   29.06 7036.75    30.8
#Mann= 4 ,-1 , 0
 2117.06     .07       0 4938.43     .15       0 4969.92    .015       0
 5030.08     .15       0
#XS Ineff= 1 ,-1
    2940    3300    32.4
Permanent Ineff=
       F
#Block Obstruct= 1 ,-1
 2177.47 2443.69   33.98
Bank Sta=4969.92,5030.08
XS Rating Curve= 0 ,0
Exp/Cntr=0.3,0.1

Type RM Length L Ch R = 1 ,23040.8 ,23.42,20,21.73
BEGIN DESCRIPTION:
Sageglen Drive
END DESCRIPTION:
XS GIS Cut Line= 6
      3170249.26    13785584.298     3171466.426    13784456.964
      3171949.24     13784062.14      3172494.84    13783566.586
     3172917.342    13783188.655     3173196.793    13782235.628
#Sta/Elev= 30
 2607.03   50.56 2765.62   55.97 2782.71    54.2 2815.17   36.69 2831.85    33.3
 2866.82   32.55 3069.96   34.97 3279.98    30.4 3532.09    31.6 3751.99   28.77
 3884.14   30.25 3969.59   28.07 4086.42   30.92 4253.31   27.65 4408.34   29.83
 4532.34   27.49 4969.38    28.1 4991.17   18.84 5002.59   18.34 5010.44   18.76
 5030.62   27.86  5579.9   28.86 5637.41   26.71 5933.11   27.29 5992.57   29.66
 6244.82   27.39 6669.45   30.71 6751.02   23.17 6850.95   31.38 7186.88   30.47
#Mann= 4 ,-1 , 0
 2607.03     .07       0 3751.99     .15       0 4969.38    .015       0
 5030.62     .15       0
#Block Obstruct= 1 ,-1
 6682.71 6870.27      28
Bank Sta=4969.38,5030.62
XS Rating Curve= 0 ,0
Exp/Cntr=0.5,0.3

Type RM Length L Ch R = 1 ,23020.8 ,98.05,90,112.93
BEGIN DESCRIPTION:
Sageglen Drive
END DESCRIPTION:
XS GIS Cut Line= 6
       3170291.9    13785584.298     3171464.973    13784491.666
       3171962.3    13784077.292     3172508.233     13783581.44
     3172947.384    13783188.616     3173219.154    13782260.473
#Sta/Elev= 30
 2639.23   51.29 2783.07   56.43 2799.28   54.65 2841.36   36.78 2863.37   33.01
 3065.05   34.97 3178.99   33.85 3254.95   30.47 3463.99   32.22 3775.31   28.97
 4099.82   30.28 4969.38    28.1 4991.17   18.84 5002.59   18.34 5010.44   18.76
 5030.62   27.86    5086   31.05 5348.73   26.79 5577.73   28.52  5638.9   26.69
 5814.03   29.11  5934.9   27.26 5996.61   29.66 6153.62   29.62 6214.51   27.19
 6576.25      31 6665.43    30.6 6734.43   22.69 6816.67   30.79 7183.54   30.03
#Mann= 4 ,-1 , 0
 2639.23     .07       0 3775.31     .15       0 4969.38    .015       0
 5030.62     .15       0
#XS Ineff= 2 , 0
       0    4951    32.5    5049       0      33
Permanent Ineff=
       F       F
#Block Obstruct= 1 ,-1
 6663.17 6852.17      28
Bank Sta=4969.38,5030.62
XS Rating Curve= 0 ,0
Exp/Cntr=0.5,0.3

Type RM Length L Ch R = 3 ,22975   ,,,
BEGIN DESCRIPTION:
Bridge at Sageglen Drive
END DESCRIPTION:
Bridge Culvert--1,0,-1,-1, 0
Deck Dist Width WeirC Skew NumUp NumDn MinLoCord MaxHiCord MaxSubmerge Is_Ogee
4,80,2.6,0, 14, 14, , , 0.95, 0, 0,0,,
    3945    4547    4854    4920    4955    4955    4968    5027    5045    5045
    5125    5183    5503    5800
   28.17   27.84   28.98    30.9   32.36   34.41   34.41   34.41   34.41   33.65
   32.98   31.01   27.44   28.07
       0       0       0       0       0   30.21   30.21   30.21   30.21       0
       0       0       0       0
    3945    4547    4854    4920    4955    4955    4968    5027    5045    5045
    5125    5183    5503    5800
   28.17   27.84   28.98    30.9   32.36   34.41   34.41   34.41   34.41   33.65
   32.98   31.01   27.44   28.07
       0       0       0       0       0   30.21   30.21   30.21   30.21       0
       0       0       0       0
Pier Skew, UpSta & Num, DnSta & Num=  ,4988.5, 4 ,4988.5, 4 , 3 , 3 , 0 ,,
    1.35    1.35     2.1     2.1
       0   28.11   28.11      31
    1.35    1.35     2.1     2.1
       0   28.11   28.11      31
Pier Skew, UpSta & Num, DnSta & Num=  ,5011.5, 4 ,5011.5, 4 , 3 , 3 , 0 ,,
    1.35    1.35     2.1     2.1
       0   28.11   28.11      31
    1.35    1.35     2.1     2.1
       0   28.11   28.11      31
BR Coef=-1 , 1 , 0 ,, 0 ,,,0.8,0,2,0,
WSPro=,,,, 1 ,,,, 0 ,,,, 0 ,,,,-1 ,-1 ,-1 , 0 , 0 , 0 , 0 , 0
BC Design=,, 0 ,, 0 ,,,,,,
BC HTab HWMax=56.43
BC Use User HTab Curves=0
BC User HTab FreeFlow(D)= 0

Type RM Length L Ch R = 1 ,22930.8 ,73.33,80,114.31
BEGIN DESCRIPTION:
Sageglen Drive
END DESCRIPTION:
XS GIS Cut Line= 6
      3170425.94     13785590.39     3171549.066    13784556.225
     3172127.513     13784051.38       3172568.5    13783648.283
       3172997.2    13783264.808     3173263.034    13782313.356
#Sta/Elev= 30
 2736.83   48.74 2763.43   54.67 2839.77   57.13 2949.21   32.73  2993.5    31.8
 3054.38   33.48  3147.4   30.59 3269.75   30.62 3445.15   33.79  3761.5   31.02
 4262.22   27.44    4334   28.93 4969.38    28.1 4991.17   18.84 5002.59   18.34
 5010.44   18.76 5030.62   27.86    5056      30  5346.6   26.65  5420.5   28.45
 5872.14   27.04 6123.42   29.61    6210   26.79  6285.1   29.69 6441.94   28.59
 6610.66   31.05 6649.91   29.31 6701.42   22.38  6778.7   30.73  7191.9   30.09
#Mann= 4 ,-1 , 0
 2736.83     .07       0  3761.5     .15       0 4969.38    .015       0
 5030.62     .15       0
#XS Ineff= 2 , 0
       0    4951      32    5049       0      33
Permanent Ineff=
       F       F
#Block Obstruct= 2 ,-1
                         6605.83 6781.12      28
Bank Sta=4969.38,5030.62
XS Rating Curve= 0 ,0
Exp/Cntr=0.5,0.3

Type RM Length L Ch R = 1 ,22850.8 ,696.07,244.51,76.33
BEGIN DESCRIPTION:
Sageglen Drive
END DESCRIPTION:
XS GIS Cut Line= 6
      3170517.32    13785602.575     3171600.223    13784600.354
     3172129.514    13784156.676     3172622.071    13783707.699
     3173036.345    13783337.128     3173307.696      13782363.6
#Sta/Elev= 30
 2796.02   49.44    2827   55.75 2855.33   55.59 3009.03   32.07 3205.67   30.86
  3428.2   34.44 3763.84   30.64 3863.09    31.6 3982.46   28.47  4173.7   30.83
 4265.56   27.55 4331.42   29.82 4536.84   27.38 4603.94    29.6 4969.38    28.1
 4991.17   18.84 5002.59   18.34 5010.44   18.76 5030.62   27.86 5275.52   29.33
 5331.24   26.31 5685.24   29.18 6203.73   26.94 6298.14   30.13    6566    30.9
 6610.37   29.69 6670.36   22.39 6736.97   30.11 6781.32   31.52 7195.18   30.58
#Mann= 4 ,-1 , 0
 2796.02     .07       0 3763.84     .15       0 4969.38    .015       0
 5030.62     .15       0
#XS Ineff= 1 ,-1
    2900    3300    32.2
Permanent Ineff=
       F
#Block Obstruct= 1 ,-1
 6581.28 6775.22      28
Bank Sta=4969.38,5030.62
XS Rating Curve= 0 ,0
Exp/Cntr=0.3,0.1

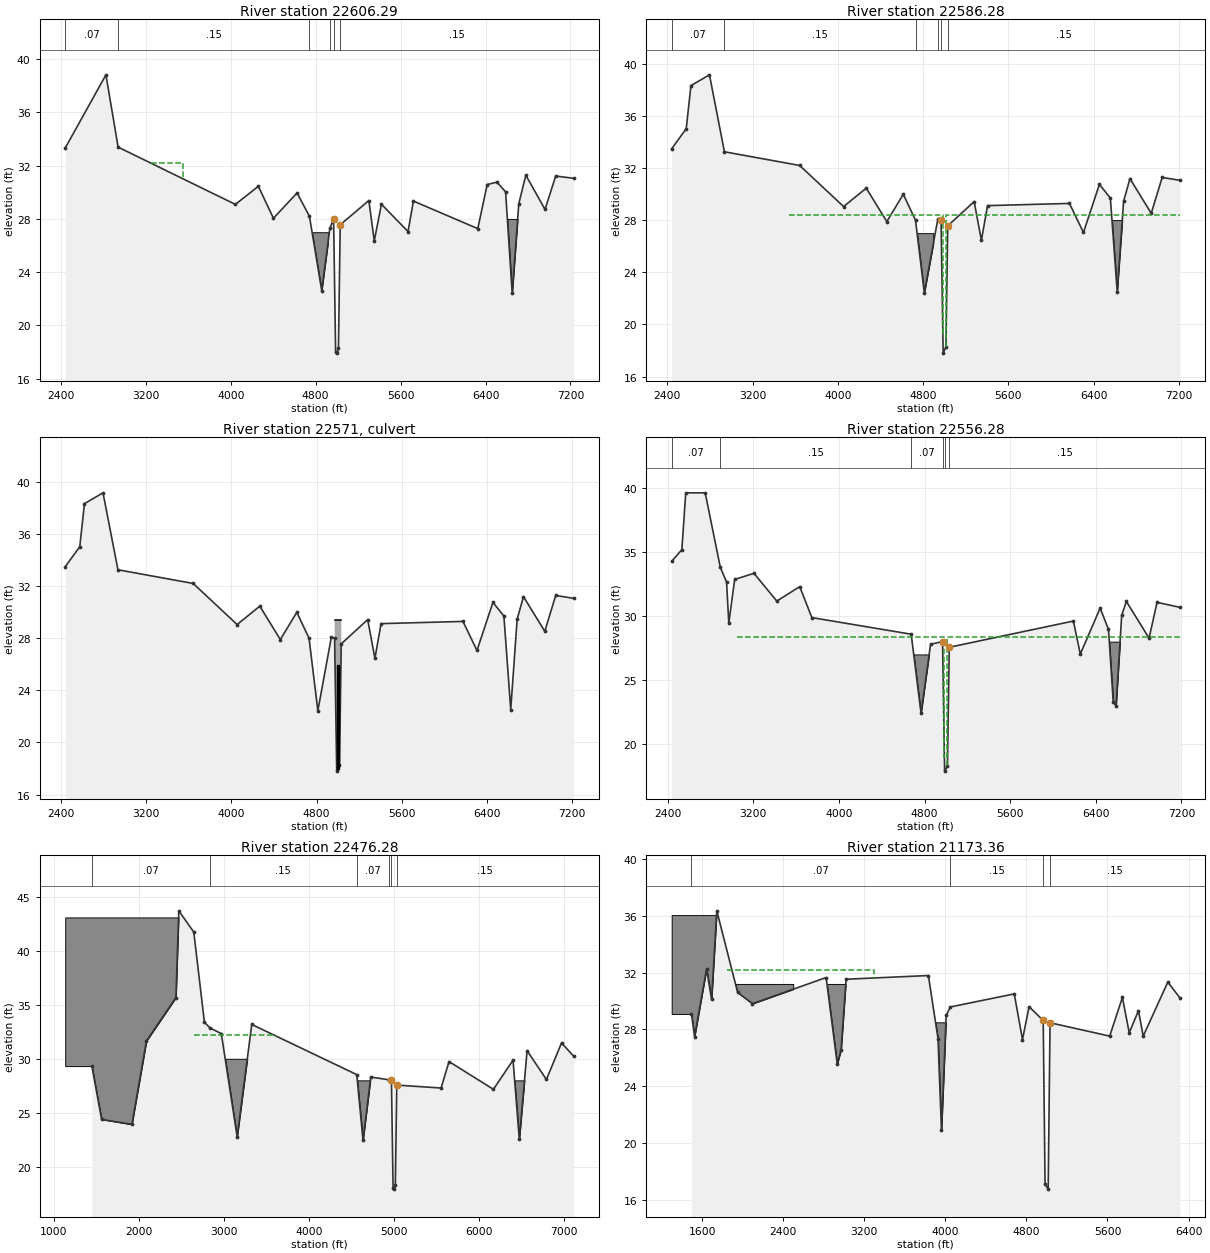
Type RM Length L Ch R = 1 ,22606.29,20.03,20.01,32.99
BEGIN DESCRIPTION:
Footbridge
END DESCRIPTION:
XS GIS Cut Line= 6
      3172771.26    13786756.603     3172378.689    13784355.112
     3172316.587    13784020.119     3172328.206    13783996.229
     3173115.897    13783355.524     3173349.566    13782411.053
#Sta/Elev= 30
  2440.3   33.32 2823.98   38.82  2938.8   33.39 4043.54   29.09 4260.02   30.45
 4401.94   28.05 4624.74   29.95 4741.16    28.2 4856.88   22.62  4933.6   27.29
 4968.77   28.01 4987.88   17.98 5002.93   17.92 5014.49   18.27 5031.23   27.56
 5300.98   29.38    5352   26.35 5419.54    29.1  5670.2   27.05 5720.64   29.34
 6327.39   27.27 6415.65   30.58 6507.78   30.76 6589.28   30.03  6651.3   22.42
 6713.33   29.13 6779.74   31.28 6960.93   28.71 7060.79   31.22 7229.26   31.05
#Mann= 6 ,-1 , 0
  2440.3     .07       0  2938.8     .15       0 4741.16     .07       0
  4933.6     .15       0 4968.77    .015       0 5031.23     .15       0
#XS Ineff= 1 ,-1
    3250    3550    32.2
Permanent Ineff=
       F
#Block Obstruct= 3 ,-1
  4742.3 4915.76      27 6556.41 6770.99      28    2900    3050    32.2
Bank Sta=4968.77,5031.23
XS Rating Curve= 0 ,0
Exp/Cntr=0.5,0.3

Type RM Length L Ch R = 1 ,22586.28,30.04,30,74.34
BEGIN DESCRIPTION:
Footbridge
END DESCRIPTION:
XS GIS Cut Line= 6
        3172791.    13786753.377     3172398.389    13784351.653
     3172367.932    13784195.635     3172343.166    13784004.366
     3173133.723    13783362.436     3173363.523    13782422.219
#Sta/Elev= 30
 2439.99   33.47  2576.7   35.01 2620.68   38.31 2794.74   39.14 2935.04   33.24
 3641.44   32.19  4053.9   29.04 4266.52   30.45 4459.42   27.89 4614.18   29.98
    4729   27.99 4811.52   22.43 4937.78   28.05 4968.77   28.01  4988.6    17.8
 5014.49   18.27 5031.23   27.56 5279.48   29.42 5347.36   26.45 5405.04   29.11
 6174.02   29.28 6305.36   27.05 6455.16   30.74 6557.99   29.69 6622.15   22.52
 6682.45   29.45  6741.9   31.18 6941.74   28.52 7044.33   31.27 7211.68   31.05
#Mann= 6 ,-1 , 0
 2439.99     .07       0 2935.04     .15       0    4729     .07       0
 4937.78     .15       0 4968.77    .015       0 5031.23     .15       0
#XS Ineff= 3 ,-1
    3542    4986    28.4 3307.32 3541.46    32.2    5014 7211.68    28.4
Permanent Ineff=
       F       F       F
#Block Obstruct= 3 ,-1
    2900    3050    32.2  4702.2 4894.95      27 6543.95 6735.24      28
Bank Sta=4968.77,5031.23
XS Rating Curve= 0 ,0
Exp/Cntr=0.5,0.3

Type RM Length L Ch R = 2 ,22571   ,,,
BEGIN DESCRIPTION:
Footbridge
END DESCRIPTION:
Bridge Culvert--1,0,-1,-1, 0
Deck Dist Width WeirC Skew NumUp NumDn MinLoCord MaxHiCord MaxSubmerge Is_Ogee
4,17,2.6,0, 3, 3, , , 0.95, 0, 0,0,,
    4969    5005    5032
   29.39   29.39   29.39
       0       0       0
    4969    5005    5032
   29.39   29.39   29.39
       0       0       0
BR Coef=-1 , 0 , 0 ,, 0 ,,,0.8,-1,,0,
WSPro=,,,, 1 ,,,, 0 ,,,, 0 ,,,,-1 ,-1 ,-1 , 0 , 0 , 0 , 0 , 0
Culvert=2,8,10,17,0.012,0.5,1,10,1,17.9,4994.75,17.97,4994.75,Culvert #1  , 0 ,4
Culvert Bottom n=0.012
Culvert=2,8,10,17,0.012,0.5,1,10,1,17.94,5005.25,17.93,5005.25,Culvert #2  , 0 ,4
Culvert Bottom n=0.012
BC Design=,, 0 ,, 0 ,,,,,,
BC HTab HWMax=39.14
BC Use User HTab Curves=0
BC User HTab FreeFlow(D)= 0

Type RM Length L Ch R = 1 ,22556.28,80.11,80,103.56
BEGIN DESCRIPTION:
Footbridge
END DESCRIPTION:
XS GIS Cut Line= 6
      3172820.61    13786748.537     3172427.939    13784346.463
     3172397.399    13784189.986     3172364.999    13784006.749
       3173158.2    13783399.957     3173397.019    13782458.507
#Sta/Elev= 30
 2437.69   34.28 2532.78   35.19 2569.12   39.63 2750.81   39.63 2892.01   33.81
 2950.67   32.66 2971.34   29.45 3026.37   32.86 3206.63   33.34 3420.01   31.17
 3634.34    32.3 3747.21   29.88 4675.55   28.58  4767.6   22.41 4856.57   27.79
 4968.77   28.01 4987.95   17.88 5014.49   18.27 5031.23   27.56 6191.11   29.61
 6255.54   27.03 6441.19   30.62 6519.03   28.95  6563.1   23.31 6589.47   22.97
 6642.23   30.05 6686.13   31.14 6898.21   28.27 6972.45   31.07 7187.11   30.68
#Mann= 6 ,-1 , 0
 2437.69     .07       0 2892.01     .15       0 4675.55     .07       0
 4968.77     .15       0 4987.95    .015       0 5031.23     .15       0
#XS Ineff= 3 ,-1
    3044    4986    28.4 2915.12 3043.36   32.65    5014 7187.11    28.4
Permanent Ineff=
       F       F       F
#Block Obstruct= 2 ,-1
 4650.83 4855.39      27 6498.39    6677      28
Bank Sta=4968.77,5031.23
XS Rating Curve= 0 ,0
Exp/Cntr=0.5,0.3

Type RM Length L Ch R = 1 ,22476.28,1429.09,1302.92,522.94
BEGIN DESCRIPTION:
Footbridge
END DESCRIPTION:
XS GIS Cut Line= 6
      3173063.93    13787704.443     3172893.603    13786699.161
     3172506.738    13784332.624     3172443.777     13783992.82
     3173192.516    13783431.713      3173438.89    13782503.168
#Sta/Elev= 30
 1448.67   29.32 1563.19   24.38 1919.11   23.92 2090.02   31.65 2436.16   35.67
 2470.22   43.71  2646.2   41.74 2770.96   33.39 2836.34   32.86 2969.84   32.33
 3155.78   22.77 3327.34   33.18  4561.3   28.53 4634.66   22.44  4725.5   28.31
 4937.78   28.05 4968.77   28.01 4987.88   17.98 5002.93   17.92 5014.49   18.27
 5031.23   27.56 5551.76   27.29 5645.34   29.74 6166.64   27.17  6397.4   29.87
 6470.99   22.55 6562.56   30.75 6789.42   28.08 6967.34   31.47 7108.17   30.25
#Mann= 6 ,-1 , 0
 1448.67     .07       0 2836.34     .15       0  4561.3     .07       0
 4937.78     .15       0 4968.77    .015       0 5031.23     .15       0
#XS Ineff= 1 ,-1
    2650    3600    32.2
Permanent Ineff=
       F
#Block Obstruct= 4 ,-1
 1135.38 2505.12    43.1 2967.83 3348.21      30 4541.45 4725.02      28
 6395.73 6598.27      28
Bank Sta=4968.77,5031.23
XS Rating Curve= 0 ,0
Exp/Cntr=0.3,0.1

Type RM Length L Ch R = 1 ,21173.36,20.1,20,20.02
BEGIN DESCRIPTION:
Grapewood Drive
END DESCRIPTION:
XS GIS Cut Line= 6
      3175089.25    13786993.645     3173848.735    13784094.243
     3173691.607    13783741.905     3173660.538    13783663.761
     3173412.915    13783086.109       3173453.9    13782519.223
#Sta/Elev= 30
 1495.57   29.09 1526.62    27.5 1644.71   32.26 1694.14   30.11 1745.72   36.34
  1951.4    30.6 2097.38   29.81 2824.33   31.65 2934.07   25.57 2972.04   26.57
 3021.24   31.53 3833.31   31.79 3928.17   27.36 3962.45    20.9 4008.75   28.98
 4050.38   29.58 4680.61    30.5 4761.83   27.29 4826.79    29.6 4966.32   28.63
 4984.47   17.11 5015.38   16.77 5033.68   28.47 5622.33   27.53  5747.6   30.25
 5814.96   27.77 5906.39   29.32 5952.91   27.53 6195.94   31.33 6315.97   30.21
#Mann= 4 ,-1 , 0
 1495.57     .07       0 4050.38     .15       0 4966.32    .015       0
 5033.68     .15       0
#XS Ineff= 1 ,-1
    1850    3300    32.2
Permanent Ineff=
       F
#Block Obstruct= 4 ,-1
 1300.34 1750.85   36.04 1925.44    2500    31.2 2796.51 3020.45    31.2
 3876.49 4010.07    28.5
Bank Sta=4966.32,5033.68
XS Rating Curve= 0 ,0
Exp/Cntr=0.5,0.3

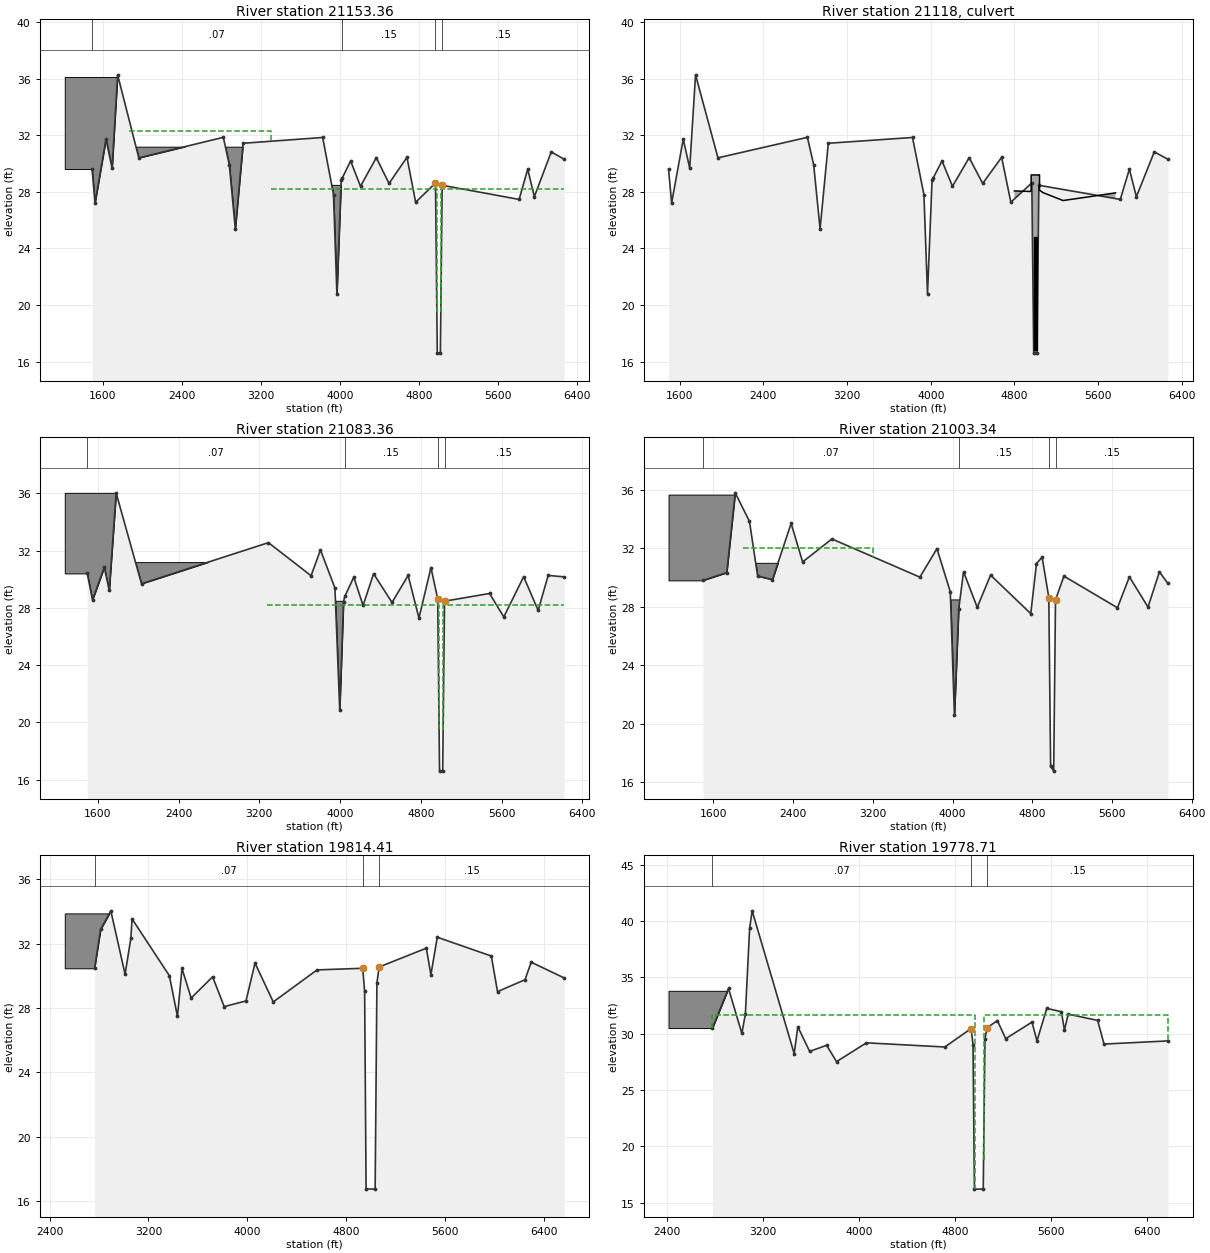
Type RM Length L Ch R = 1 ,21153.36,70.36,70,70.07
BEGIN DESCRIPTION:
Grapewood Drive
END DESCRIPTION:
XS GIS Cut Line= 6
     3175107.638    13786985.778     3173867.091    13784086.303
     3173710.054     13783734.17     3173679.025    13783656.125
     3173431.558    13783078.839     3173474.032    13782559.488
#Sta/Elev= 30
 1494.62   29.62 1524.26   27.22  1635.2   31.73  1696.9   29.68  1752.8   36.28
 1966.92   30.41 2821.74   31.86 2881.72   29.92 2942.82   25.39 3021.48   31.44
 3826.08   31.85 3935.24   27.81 3969.52    20.8  4013.1   28.84 4024.04   28.99
  4108.3   30.19  4208.2    28.4 4367.82   30.42 4496.92    28.6    4678   30.45
 4765.76   27.27 4966.32   28.63  4984.4    16.6  5015.6    16.6 5033.68   28.47
 5811.72   27.47 5898.82   29.61 5965.52   27.66  6136.6   30.83  6267.1   30.31
#Mann= 4 ,-1 , 0
 1494.62     .07       0 4024.04     .15       0 4966.32    .015       0
 5033.68     .15       0
#XS Ineff= 3 ,-1
    3303    4980    28.2 1868.29 3302.44   32.28    5020  6267.1    28.2
Permanent Ineff=
       F       F       F
#Block Obstruct= 4 ,-1
 1218.43 1757.68   36.13 1930.89    2500    31.2  2776.9 3021.58    31.2
  3884.4 4013.04    28.5
Bank Sta=4966.32,5033.68
XS Rating Curve= 0 ,0
Exp/Cntr=0.5,0.3

Type RM Length L Ch R = 2 ,21118   ,,,
BEGIN DESCRIPTION:
Culverts at Grapewood Drive
END DESCRIPTION:
Bridge Culvert--1,0,-1,-1, 0
Deck Dist Width WeirC Skew NumUp NumDn MinLoCord MaxHiCord MaxSubmerge Is_Ogee
5,40,2.6,0, 12, 12, , , 0.95, 0, 0,0,,
    4800    4952    4960    4960    4969    5016    5036    5040    5040    5073
    5265    5766
   28.07   28.03   28.12    29.2    29.2    29.2    29.2    29.2   28.12   27.95
   27.39   27.93
       0       0       0       0       0       0       0       0       0       0
       0       0
    4800    4952    4960    4960    4969    5016    5036    5040    5040    5073
    5265    5766
   28.07   28.03   28.12    29.2    29.2    29.2    29.2    29.2   28.12   27.95
   27.39   27.93
       0       0       0       0       0       0       0       0       0       0
       0       0
BR Coef=-1 , 0 , 0 ,, 0 ,,,0.8,-1,,0,
WSPro=,,,, 1 ,,,, 0 ,,,, 0 ,,,,-1 ,-1 ,-1 , 0 , 0 , 0 , 0 , 0
Multiple Barrel Culv=2,8,10,40,0.012,0.4,1,8,1,16.82,16.63, 3,Culvert #1  , 0 ,5
  4989.5  4989.5    5000    5000  5010.5  5010.5
Culvert Bottom n=0.012
BC Design=,, 0 ,, 0 ,,,,,,
BC HTab HWMax=36.28
BC Use User HTab Curves=0
BC User HTab FreeFlow(D)= 0

Type RM Length L Ch R = 1 ,21083.36,80.41,80.01,80.08
BEGIN DESCRIPTION:
Grapewood Drive
END DESCRIPTION:
XS GIS Cut Line= 6
     3175171.995    13786958.243      3173931.34    13784058.515
      3173774.62    13783707.097     3173743.729      13783629.4
     3173497.721    13783055.517     3173504.231     13782579.62
#Sta/Elev= 30
 1495.73   30.41 1547.79   28.56 1664.38   30.84 1713.39   29.22 1781.95   36.03
 2033.02   29.69 3289.91   32.56  3712.2   30.25 3805.18   32.05 3948.52   29.39
 3996.01   20.88 4033.61   28.44 4046.01    28.8 4135.23   30.15 4227.21   28.17
 4331.14   30.39  4513.8   28.38 4673.32   30.27 4780.63   27.29  4899.4   30.82
 4966.32   28.63  4984.4    16.6  5015.6    16.6 5033.68   28.47 5479.73   29.01
 5620.67   27.37 5817.17   30.18 5960.78   27.83 6060.18   30.27 6218.47   30.17
#Mann= 4 ,-1 , 0
 1495.73     .07       0 4046.01     .15       0 4966.32    .015       0
 5033.68     .15       0
#XS Ineff= 3 ,-1
    3274    4980    28.2  1887.8 3273.17   32.14    5020 6218.47    28.2
Permanent Ineff=
       F       F       F
#Block Obstruct= 3 ,-1
 1273.04 1784.98   36.04 1945.19 3092.45    31.2 3925.21  4032.7    28.5
Bank Sta=4966.32,5033.68
XS Rating Curve= 0 ,0
Exp/Cntr=0.5,0.3

Type RM Length L Ch R = 1 ,21003.34,1290.85,1188.94,968.86
BEGIN DESCRIPTION:
Grapewood Drive
END DESCRIPTION:
XS GIS Cut Line= 6
     3175245.546    13786926.774     3174004.767    13784026.757
     3173848.409    13783676.156     3173817.677    13783598.856
     3173571.253    13783024.003     3173579.726    13782604.785
#Sta/Elev= 30
 1495.72    29.8 1734.34   30.33 1819.48   35.78 1962.41   33.83 2044.38    30.1
  2192.6   29.85 2380.48   33.69 2495.71   31.06 2789.73   32.63 3672.54   30.02
 3843.93   31.97 3977.72   29.02  4019.3   20.59  4062.1   27.82 4110.71   30.39
 4247.83   27.96 4381.95   30.16 4785.37   27.53 4842.72   30.95 4899.54   31.38
 4966.32   28.63 4984.47   17.11 5015.38   16.77 5033.68   28.47 5118.01   30.09
 5655.06   27.93 5775.12   30.04 5961.71   27.98 6076.64   30.38 6161.87   29.59
#Mann= 4 ,-1 , 0
 1495.72     .07       0  4062.1     .15       0 4966.32    .015       0
 5033.68     .15       0
#XS Ineff= 1 ,-1
    1900    3200      32
Permanent Ineff=
       F
#Block Obstruct= 3 ,-1
 1150.17 1825.94   35.66 2001.63 2267.37      31 3949.19 4063.95    28.5
Bank Sta=4966.32,5033.68
XS Rating Curve= 0 ,0
Exp/Cntr=0.3,0.1

Type RM Length L Ch R = 1 ,19814.41,37.1,35.7,34.14
BEGIN DESCRIPTION:
Scarsdale Blvd
END DESCRIPTION:
XS GIS Cut Line= 6
       3176602.3    13785124.663     3175316.754    13783904.795
     3175113.581     13783683.99     3174922.496    13783445.966
     3174589.218    13782982.458     3174158.794     13782248.88
#Sta/Elev= 30
 2764.26   30.46 2813.02   32.87 2896.02   34.03 3011.22   30.09 3058.34   32.34
 3067.58   33.53 3369.54      30 3434.96   27.47  3471.6   30.45 3545.82   28.61
 3719.48   29.93  3813.1   28.08 3989.32   28.43 4062.52   30.78    4210   28.37
 4564.32   30.36 4933.55   30.46 4949.21   29.03 4960.97   16.75 5034.25   16.74
 5048.51   29.55 5066.45   30.54 5448.12   31.71  5485.2   30.06 5536.92   32.39
 5974.12   31.22 6024.24   29.01 6246.54   29.75 6296.48   30.84  6563.3   29.86
#Mann= 3 ,-1 , 0
 2764.26     .07       0 4933.55    .015       0 5066.45     .15       0
#Block Obstruct= 1 ,-1
 2523.32 2887.37   33.87
Bank Sta=4933.55,5066.45
XS Rating Curve= 0 ,0
Exp/Cntr=0.5,0.3

Type RM Length L Ch R = 1 ,19778.71,185.51,166.38,168.93
BEGIN DESCRIPTION:
Scarsdale Blvd
END DESCRIPTION:
XS GIS Cut Line= 6
     3176623.022     13785102.97     3175338.082    13783883.684
      3175136.57    13783664.706     3174946.779    13783428.288
     3174614.349    13782966.008     3174184.669    13782233.698
#Sta/Elev= 30
 2780.54    30.5 2914.32   34.02 3025.61   30.02 3054.64   31.75 3090.11   39.35
 3111.16   40.91 3460.59   28.24 3491.47   30.61 3589.61   28.43 3730.75   28.97
 3813.41   27.52 4062.18   29.19 4714.75   28.82 4933.55   30.46 4949.21   29.03
 4960.97    16.2 5034.25    16.2 5048.51   29.55 5066.45   30.54 5151.89   31.16
  5221.3   29.56 5440.02   31.03 5481.38   29.36 5563.04   32.25 5684.73   31.95
 5710.05   30.31 5741.08   31.74 5986.23   31.18 6039.54   29.08 6571.25   29.36
#Mann= 3 ,-1 , 0
 2780.54     .07       0 4933.55    .015       0 5066.45     .15       0
#XS Ineff= 2 , 0
       0    4963   31.65    5037       0   31.65
Permanent Ineff=
       F       F
#Block Obstruct= 1 ,-1
 2415.24 2910.13   33.81
Bank Sta=4933.55,5066.45
XS Rating Curve= 0 ,0
Exp/Cntr=0.5,0.3