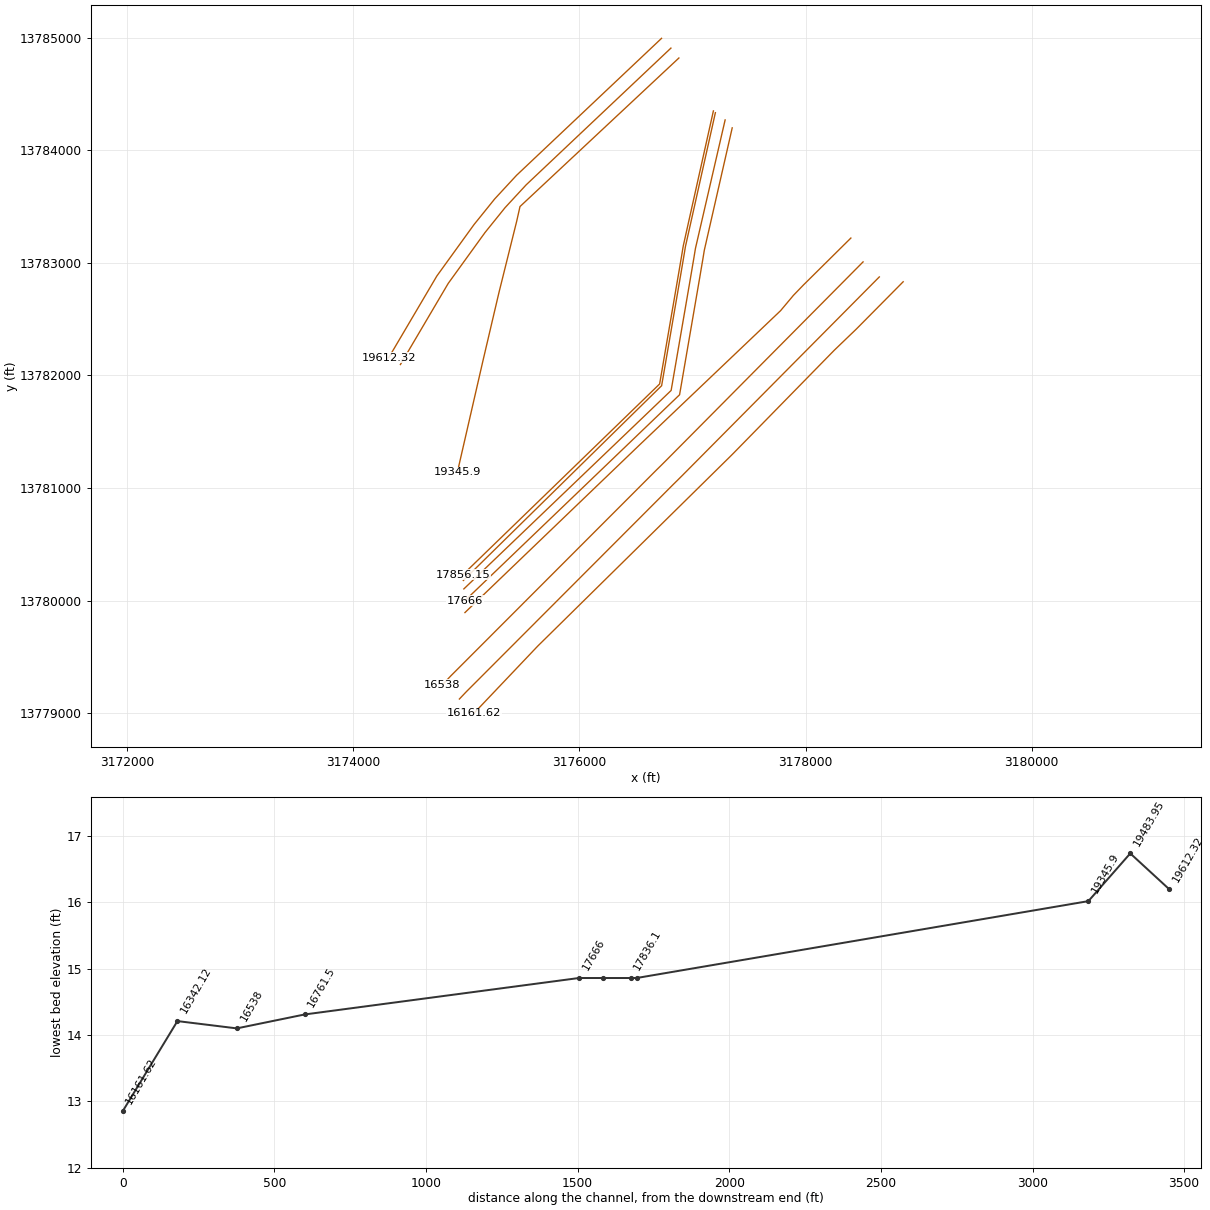
HEC-RAS study A119-00-00.prj: A119-00-00

--- A119-00-00.g01 (geometry) --- (continued)

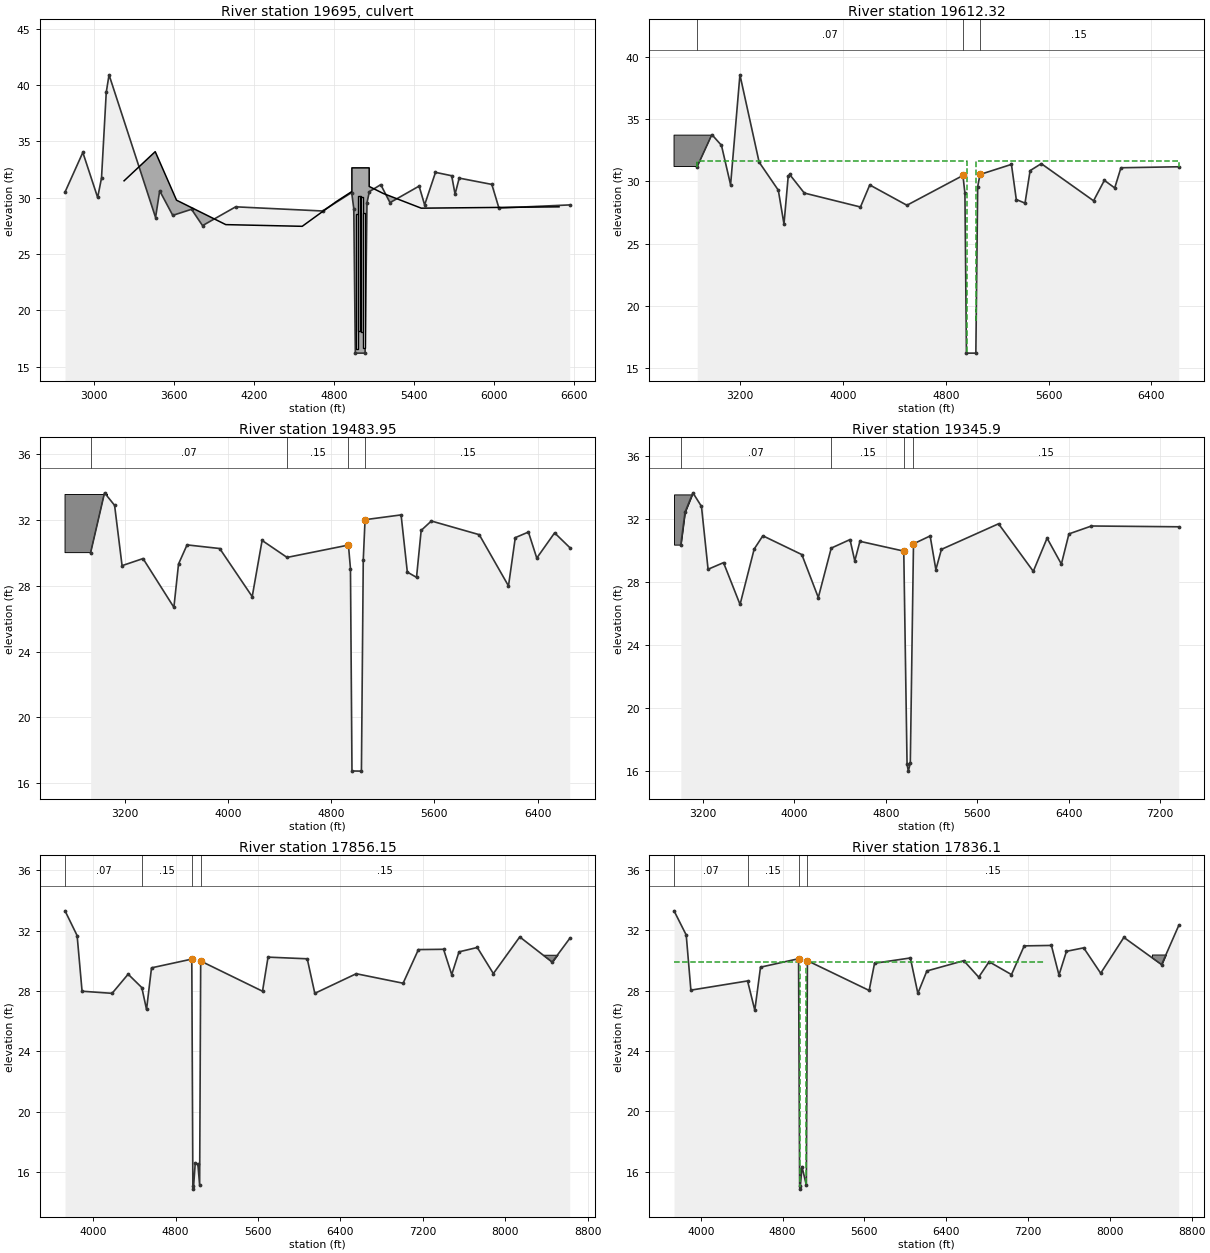
Type RM Length L Ch R = 2 ,19695   ,,,
BEGIN DESCRIPTION:
Culverts at Scarsdale Blvd
END DESCRIPTION:
Bridge Culvert--1,0,-1,-1, 0
Deck Dist Width WeirC Skew NumUp NumDn MinLoCord MaxHiCord MaxSubmerge Is_Ogee
5,110,2.6,0, 14, 14, , , 0.95, 0, 0,0,,
    3224    3458    3618    3988    4562    4820    4935    4935    5000    5065
    5065    5170    5456    6491
    31.5   34.09   29.78   27.61   27.46   29.67   30.55   32.65   32.65   32.65
      31   30.38   29.07   29.19
       0       0       0       0       0       0       0       0       0       0
       0       0       0       0
    3224    3458    3618    3988    4562    4820    4935    4935    5000    5065
    5065    5170    5456    6491
    31.5   34.09   29.78   27.61   27.46   29.67   30.55   32.65   32.65   32.65
      31   30.38   29.07   29.19
       0       0       0       0       0       0       0       0       0       0
       0       0       0       0
BR Coef=-1 , 0 , 0 ,, 0 ,,,0.8,-1,,0,
WSPro=,,,, 1 ,,,, 0 ,,,, 0 ,,,,-1 ,-1 ,-1 , 0 , 0 , 0 , 0 , 0
Culvert=2,12,12,110,0.012,0.5,1,10,1,16.58,4974.5,16.3,4974.5,Culvert #1  , 0 ,5
Culvert Bottom n=0.012
Culvert=2,12,12,110,0.012,0.5,1,10,1,18.18,4987.5,18.06,4987.5,Culvert #2  , 0 ,5
Culvert Bottom n=0.012
Culvert=2,12,12,110,0.012,0.5,1,10,1,18.16,5000,18.11,5000,Culvert #3  , 0 ,5
Culvert Bottom n=0.012
Culvert=2,12,12,110,0.012,0.5,1,10,1,18.07,5012.5,18.08,5012.5,Culvert #4  , 0 ,5
Culvert Bottom n=0.012
Culvert=2,12,12,110,0.012,0.5,1,10,1,16.65,5025.5,16.65,5025.5,Culvert #5  , 0 ,5
Culvert Bottom n=0.012
BC Design=,, 0 ,, 0 ,,,,,,
BC HTab HWMax=40.91
BC Use User HTab Curves=0
BC User HTab FreeFlow(D)= 0

Type RM Length L Ch R = 1 ,19612.32,148.41,128.37,129.78
BEGIN DESCRIPTION:
Scarsdale Blvd
END DESCRIPTION:
XS GIS Cut Line= 6
     3176726.631    13784994.503     3175444.721    13783778.125
     3175251.513    13783568.284     3175068.195      13783339.9
     3174740.002    13782883.755     3174314.043    13782157.788
#Sta/Elev= 30
 2864.93   31.18 2978.92   33.74 3053.51   32.88 3124.56   29.71 3197.35   38.54
 3346.83   31.53 3496.21   29.28  3540.3   26.56 3573.37    30.4 3584.68   30.54
 3698.56   29.05  4135.8   27.93 4208.21    29.7 4497.53   28.07 4933.55   30.46
 4949.21   29.03 4960.97    16.2 5034.25    16.2 5048.51   29.55 5066.45   30.54
 5311.39   31.35 5349.15   28.53 5417.03   28.24 5456.72   30.85 5543.72   31.41
 5950.75   28.43 6034.89   30.07 6115.48   29.46 6163.93   31.08 6613.96   31.16
#Mann= 3 ,-1 , 0
 2864.93     .07       0 4933.55    .015       0 5066.45     .15       0
#XS Ineff= 2 , 0
       0    4963   31.65    5037       0   31.65
Permanent Ineff=
       F       F
#Block Obstruct= 1 ,-1
  2684.3 2986.35    33.7
Bank Sta=4933.55,5066.45
XS Rating Curve= 0 ,0
Exp/Cntr=0.5,0.3

Type RM Length L Ch R = 1 ,19483.95,131.98,138.05,396.28
BEGIN DESCRIPTION:
Scarsdale Blvd
END DESCRIPTION:
XS GIS Cut Line= 6
     3176809.519     13784907.73     3175530.032    13783693.678
     3175343.467    13783491.146     3175165.328     13783269.19
     3174840.524    13782817.954     3174417.543     13782097.06
#Sta/Elev= 30
 2934.08      30 3041.91   33.63 3119.92   32.87 3177.85   29.21  3340.5   29.64
 3579.79   26.68 3615.77   29.31 3681.74   30.47  3935.2   30.25 4187.23   27.33
 4263.91   30.74 4457.51   29.71 4933.55   30.46 4949.21   29.03 4960.97   16.75
 5034.25   16.74 5048.51   29.55  5062.4      32 5341.88   32.29 5390.23   28.82
 5461.57    28.5 5497.64   31.35 5576.63   31.92 5948.04   31.09 6174.85   27.98
 6227.54   30.91 6329.43   31.25 6394.13   29.67 6532.54    31.2 6649.77   30.31
#Mann= 4 ,-1 , 0
 2934.08     .07       0 4457.51     .15       0 4933.55    .015       0
  5062.4     .15       0
#XS Ineff= 1 ,-1
    5250    6525    30.6
Permanent Ineff=
       F
#Block Obstruct= 1 ,-1
 2735.49 3058.02   33.53
Bank Sta=4933.55,5062.4
XS Rating Curve= 0 ,0
Exp/Cntr=0.3,0.1

Type RM Length L Ch R = 1 ,19345.9 ,1206.52,1489.76,1538.15
XS GIS Cut Line= 6
      3176880.08    13784819.967     3175474.997    13783500.474
     3175445.956    13783370.449     3175288.211    13782733.527
     3175147.683     13782131.67     3174920.793    13781138.792
#Sta/Elev= 30
 3008.31   30.36 3044.78   32.41 3113.84   33.64 3188.72   32.78  3246.4    28.8
 3381.56   29.22 3525.96   26.57  3649.5   30.08  3725.3   30.92  4066.3   29.73
  4210.2   27.01 4323.24   30.14 4487.42   30.68 4529.12   29.33 4574.18   30.57
  4957.5   29.95 4986.22   16.46 4997.32   16.02 5014.68   16.52  5042.5   30.41
 5188.08   30.91 5238.18   28.78 5286.72   30.06 5786.14   31.68 6090.02   28.67
  6210.6   30.77 6335.52   29.13 6401.59   31.04 6598.79   31.54 7361.74   31.49
#Mann= 4 ,-1 , 0
 3008.31     .07       0 4323.24     .15       0  4957.5    .015       0
  5042.5     .15       0
#XS Ineff= 1 ,-1
    5150    6450    30.6
Permanent Ineff=
       F
#Block Obstruct= 1 ,-1
 2948.81 3113.77   33.54
Bank Sta=4957.5,5042.5
XS Rating Curve= 0 ,0
Exp/Cntr=0.3,0.1

Type RM Length L Ch R = 1 ,17856.15,20.21,20.05,20.6
BEGIN DESCRIPTION:
Nyack Drive
END DESCRIPTION:
XS GIS Cut Line= 6
      3177185.06    13784350.013      3176918.28    13783149.293
     3176904.263     13783063.53     3176874.788    13782889.055
     3176709.649    13781924.572     3174970.918    13780231.578
#Sta/Elev= 30
 3726.22   33.31 3843.62   31.67 3891.66   27.98 4183.07   27.84 4338.88   29.11
 4471.67   28.22 4517.43   26.77  4565.8   29.53 4956.82   30.11 4967.17   15.09
 4972.43   14.86 4989.91   16.57    5016   16.51 5032.93   15.12 5043.18   29.98
 5643.35   27.98 5696.84   30.24 6077.43   30.13 6150.88   27.84 6552.95   29.14
 7007.94   28.51 7156.52   30.74 7400.88   30.76  7479.7   29.08 7550.52   30.59
 7728.13   30.88 7884.03   29.15 8140.31   31.58 8455.04   29.91  8625.4   31.48
#Mann= 4 ,-1 , 0
 3726.22     .07       0 4471.67     .15       0 4956.82    .015       0
 5043.18     .15       0
#XS Ineff= 1 ,-1
 7370.73 8121.95    30.6
Permanent Ineff=
       F
#Block Obstruct= 1 ,-1
  8371.1 8557.74    30.4
Bank Sta=4956.82,5043.18
XS Rating Curve= 0 ,0
Exp/Cntr=0.5,0.3

Type RM Length L Ch R = 1 ,17836.1 ,92.84,90.1,92.72
BEGIN DESCRIPTION:
Nyack Drive
END DESCRIPTION:
XS GIS Cut Line= 6
      3177202.67    13784334.353     3176937.923    13783145.486
     3176923.992    13783060.251     3176894.505    13782885.702
     3176727.282    13781909.046     3174974.094    13780179.468
#Sta/Elev= 30
 3739.11   33.28 3858.24   31.68 3903.78   28.03 4458.08   28.64  4528.9    26.7
 4584.66   29.55 4956.82   30.11 4967.17   15.09 4972.43   14.86 4989.91   16.35
 5032.93   15.12 5043.18   29.98 5646.98   28.01 5699.78   29.81 6049.74   30.16
 6123.18   27.82 6211.36    29.3 6572.33   29.98 6718.35   28.89 6819.82   29.91
 7038.51   29.06 7163.08   30.96 7428.93   30.99    7503   29.03 7576.14    30.6
 7744.63   30.83 7910.91   29.15 8137.51   31.52 8506.43   29.72  8674.1   32.31
#Mann= 4 ,-1 , 0
 3739.11     .07       0 4458.08     .15       0 4956.82    .015       0
 5043.18     .15       0
#XS Ineff= 3 ,-1
 3739.11    4969    29.9    5030    7359    29.9 7360.98 8102.44    30.4
Permanent Ineff=
       F       F       F
#Block Obstruct= 1 ,-1
  8411.6 8558.06   30.39
Bank Sta=4956.82,5043.18
XS Rating Curve= 0 ,0
Exp/Cntr=0.5,0.3

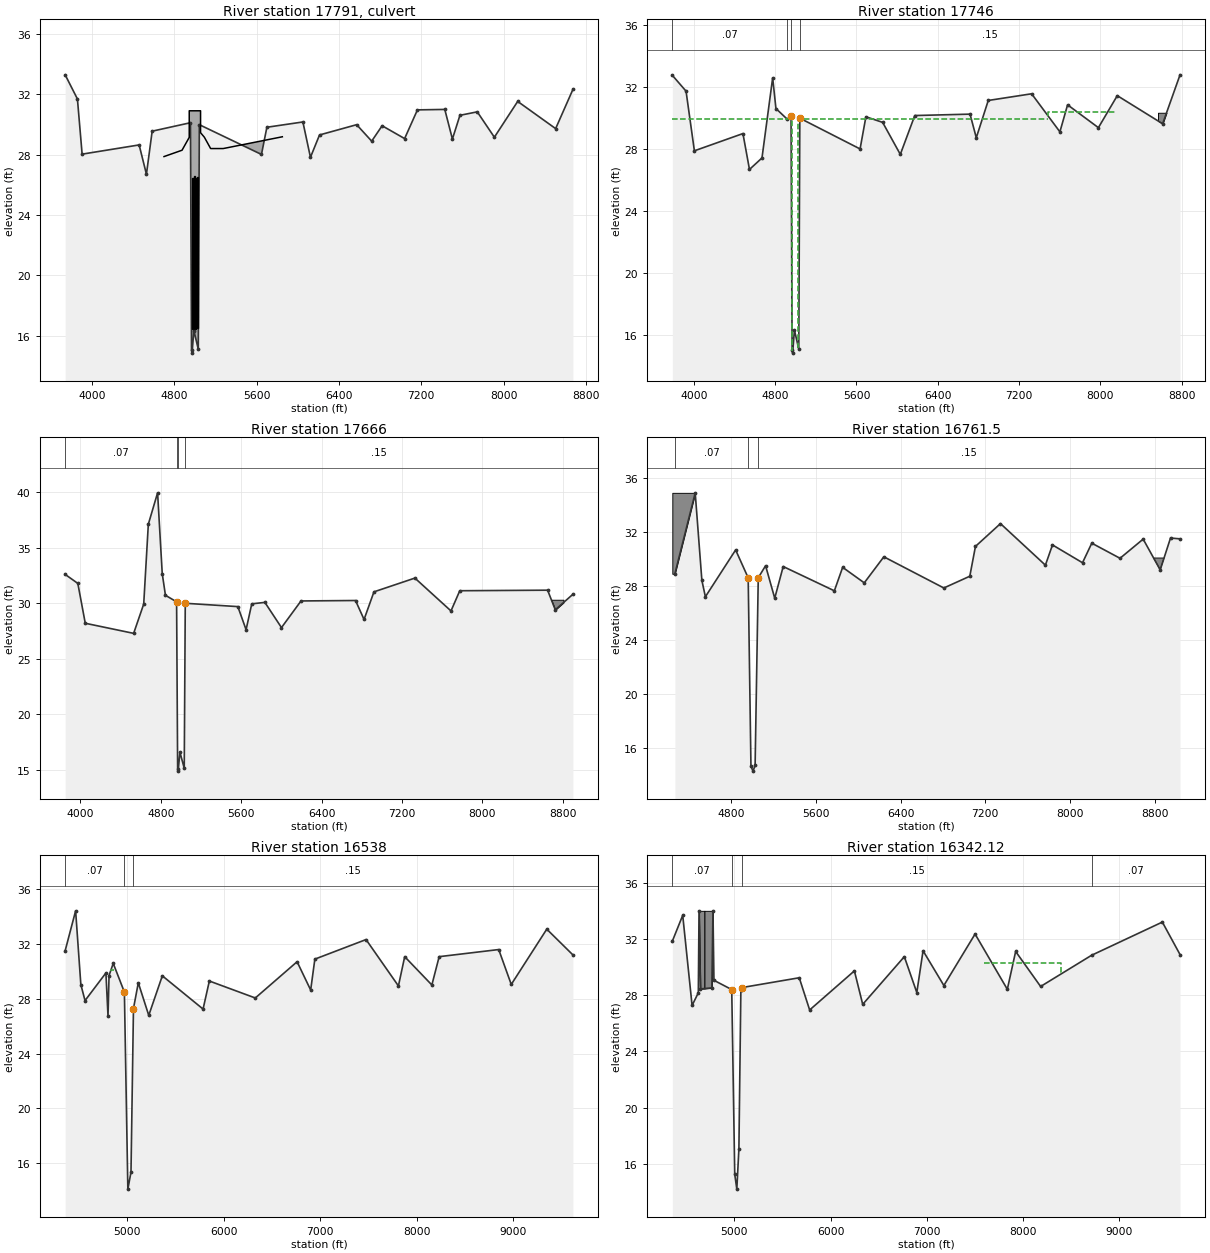
Type RM Length L Ch R = 2 ,17791   ,,,
BEGIN DESCRIPTION:
Culverts at Nyack Drive
END DESCRIPTION:
Bridge Culvert--1,0,-1,-1, 0
Deck Dist Width WeirC Skew NumUp NumDn MinLoCord MaxHiCord MaxSubmerge Is_Ogee
4,60,2.6,0, 11, 11, , , 0.95, 0, 0,0,,
    4700    4875    4945    4945    5000    5055    5055    5092    5153    5275
    5850
   27.87   28.29   29.14    30.9    30.9    30.9   29.45   29.15    28.4    28.4
   29.18
       0       0       0       0       0       0       0       0       0       0
       0
    4700    4875    4945    4945    5000    5055    5055    5092    5153    5275
    5850
   27.87   28.29   29.14    30.9    30.9    30.9   29.45   29.15    28.4    28.4
   29.18
       0       0       0       0       0       0       0       0       0       0
       0
Culvert=2,10,10,60,0.012,0.5,1,10,1,16.43,4978.5,16.46,4978.5,Culvert #1  , 0 ,4
Culvert Bottom n=0.012
Culvert=2,10,10,60,0.012,0.5,1,10,1,16.47,4989.5,16.41,4989.5,Culvert #2  , 0 ,4
Culvert Bottom n=0.012
Culvert=2,10,10,60,0.012,0.5,1,10,1,16.57,5000,16.45,5000,Culvert #3  , 0 ,4
Culvert Bottom n=0.012
Culvert=2,10,10,60,0.012,0.5,1,10,1,16.45,5010.5,16.39,5010.5,Culvert #4  , 0 ,4
Culvert Bottom n=0.012
Culvert=2,10,10,60,0.012,0.5,1,10,1,16.51,5021.5,16.48,5021.5,Culvert #5  , 0 ,4
Culvert Bottom n=0.012
BC Design=,, 0 ,, 0 ,,,,,,
BC HTab HWMax=33.66
BC Use User HTab Curves=0
BC User HTab FreeFlow(D)= 0

Type RM Length L Ch R = 1 ,17746   ,78.87,80,82.42
BEGIN DESCRIPTION:
Nyack Drive
END DESCRIPTION:
XS GIS Cut Line= 6
       3177288.8    13784269.758     3177026.317    13783128.354
     3177012.775    13783045.497     3176983.231    13782870.612
     3176811.401    13781867.049     3174978.511    13780104.081
#Sta/Elev= 30
    3789   32.74 3924.01   31.72 4006.03   27.88 4483.57   28.99 4547.95   26.68
 4670.96   27.42 4776.08   32.58  4808.2    30.6  4921.6    29.9 4956.82   30.11
 4967.17   15.09 4972.43   14.86 4989.91   16.35 5032.93   15.12 5043.18   29.98
 5635.83      28 5693.09   30.07 5857.75   29.71 6031.51   27.65 6173.84   30.15
 6717.47   30.24 6778.81   28.72  6896.6   31.12 7323.06   31.55 7601.28    29.1
 7676.78   30.84 7979.87   29.37 8165.71   31.43 8611.83   29.62 8782.82   32.77
#Mann= 4 ,-1 , 0
    3789     .07       0  4921.6     .15       0 4956.82    .015       0
 5043.18     .15       0
#XS Ineff= 3 ,-1
    3789    4969    29.9    5030    7486    29.9  7487.8 8141.46    30.4
Permanent Ineff=
       F       F       F
#Block Obstruct= 1 ,-1
 8566.08 8677.12   30.33
Bank Sta=4956.82,5043.18
XS Rating Curve= 0 ,0
Exp/Cntr=0.5,0.3

Type RM Length L Ch R = 1 ,17666   ,1126.45,904.49,417.78
BEGIN DESCRIPTION:
Nyack Drive
END DESCRIPTION:
XS GIS Cut Line= 6
      3177351.44    13784199.291      3177104.89    13783113.125
     3177091.693    13783032.381     3177062.098    13782857.198
     3176885.988    13781828.639     3174988.185    13779999.919
#Sta/Elev= 30
 3848.07   32.58 3973.96   31.77 4048.01   28.18 4529.47   27.27 4629.66   29.91
 4675.54    37.1 4767.68   39.93 4813.97   32.65  4845.8    30.7 4956.82   30.11
 4967.17   15.09 4972.43   14.86 4989.91   16.57 5032.93   15.12 5043.18   29.98
 5566.24   29.68 5648.28    27.6 5704.84   29.93 5835.32   30.06 6000.49   27.79
 6194.95   30.19  6737.3   30.23  6822.3   28.52 6920.63   31.01 7328.12   32.25
 7687.35   29.29 7774.85   31.11 8648.92   31.16  8725.1   29.39 8900.38   30.79
#Mann= 4 ,-1 , 0
 3848.07     .07       0 4956.82     .15       0 4967.17    .015       0
 5043.18     .15       0
#XS Ineff= 1 ,-1
    7500    8200    30.4
Permanent Ineff=
       F
#Block Obstruct= 1 ,-1
 8678.44 8806.81    30.3
Bank Sta=4956.82,5043.18
XS Rating Curve= 0 ,0
Exp/Cntr=0.3,0.1

Type RM Length L Ch R = 1 ,16761.5 ,229.02,223.5,231.78
XS GIS Cut Line= 6
      3178400.62     13783220.58     3177980.368    13782802.776
     3177891.975    13782710.751     3177779.048    13782575.543
     3176521.495    13781372.774     3174988.334    13779894.114
#Sta/Elev= 30
 4270.72   28.93 4462.52   34.92  4525.5   28.44 4558.58   27.23    4844    30.7
 4962.44   28.63 4988.53   14.67 5008.02   14.31 5027.78   14.73 5057.56   28.64
 5126.64   29.53 5212.96   27.12 5292.82   29.47 5775.56   27.67 5853.82   29.41
  6057.8   28.26 6242.48   30.19  6808.6   27.88 7053.51   28.75 7106.94   30.96
 7343.01   32.65 7766.93   29.57 7833.73   31.07 8117.06   29.75 8204.65    31.2
    8471   30.08  8689.4    31.5  8850.2   29.22 8947.35   31.58 9037.26   31.52
#Mann= 3 ,-1 , 0
 4270.72     .07       0 4962.44    .015       0 5057.56     .15       0
#XS Ineff= 1 ,-1
    7600    8200    30.3
Permanent Ineff=
       F
#Block Obstruct= 2 ,-1
 4246.57 4461.21   34.93    8300 8920.83    30.1
Bank Sta=4962.44,5057.56
XS Rating Curve= 0 ,0
Exp/Cntr=0.3,0.1

Type RM Length L Ch R = 1 ,16538   ,195.88,195.88,195.88
XS GIS Cut Line= 6
      3178508.48   13783008.7658      3176760.95   13781239.3002
    3176722.7458   13781201.0491   3176676.57099   13781155.4752
   3174862.34818   13779330.7088   3174788.06316   13779252.1361
#Sta/Elev= 30
 4360.13   31.53 4468.26   34.44 4522.32   29.05 4565.57   27.88 4781.83    29.9
 4803.46   26.74 4814.27   29.71 4857.52    30.6 4972.98    28.5  5008.9    14.1
 5041.34   15.34    5067    27.3 5117.03   29.18 5225.16    26.8 5365.73   29.69
 5787.44   27.26 5852.31   29.31 6328.08   28.07  6760.6   30.72 6901.17   28.65
 6944.42   30.91 7474.25   32.34 7809.45   28.95 7874.33   31.09 8155.47   29.02
 8231.16   31.09 8847.49   31.61 8977.25   29.06 9344.89    33.1 9615.21   31.22
#Mann= 3 ,-1 , 0
 4360.13     .07       0 4972.98    .015       0    5067     .15       0
#XS Ineff= 2 ,-1
 4831.42 4861.82   30.15    7600    8300    30.3
Permanent Ineff=
       F       F
Bank Sta=4972.98,5067
XS Rating Curve= 0 ,0
Exp/Cntr=0.3,0.1

Type RM Length L Ch R = 1 ,16342.12,180.5,180.5,180.5
BEGIN DESCRIPTION:
Astoria Blvd
END DESCRIPTION:
XS GIS Cut Line= 6
   3178651.97444   13782875.3224   3176912.02989   13781113.5479
   3176873.82224   13781075.2969   3176835.34478   13781037.3174
   3174998.57499   13779189.2495   3174939.14721   13779126.3916
#Sta/Elev= 30
 4355.94   31.84 4464.07   33.68 4561.39   27.27 4626.26   28.17  4633.5      34
 4647.89   28.45 4766.83   28.52  4778.5      34 4788.46   29.06  4973.5    28.4
 5004.71   15.26 5026.34   14.21 5047.97   17.08  5068.5    28.4    5077   28.54
 5675.11   29.24 5783.24   26.95  6248.2   29.73  6334.7   27.35 6767.21   30.74
 6896.97   28.19 6961.85   31.16  7178.1   28.69 7502.49   32.35 7837.69   28.42
 7924.19   31.11  8183.7   28.62 8713.53   30.84 9448.81    33.2 9632.63   30.89
#Mann= 4 ,-1 , 0
 4355.94     .07       0  4973.5    .015       0    5077     .15       0
 8713.53     .07       0
#XS Ineff= 1 ,-1
    7600    8400    30.3
Permanent Ineff=
       F
#Block Obstruct= 2 ,-1
  4633.5    4690      34    4690  4778.5      34
Bank Sta=4973.5,5077
XS Rating Curve= 0 ,0
Exp/Cntr=0.5,0.3

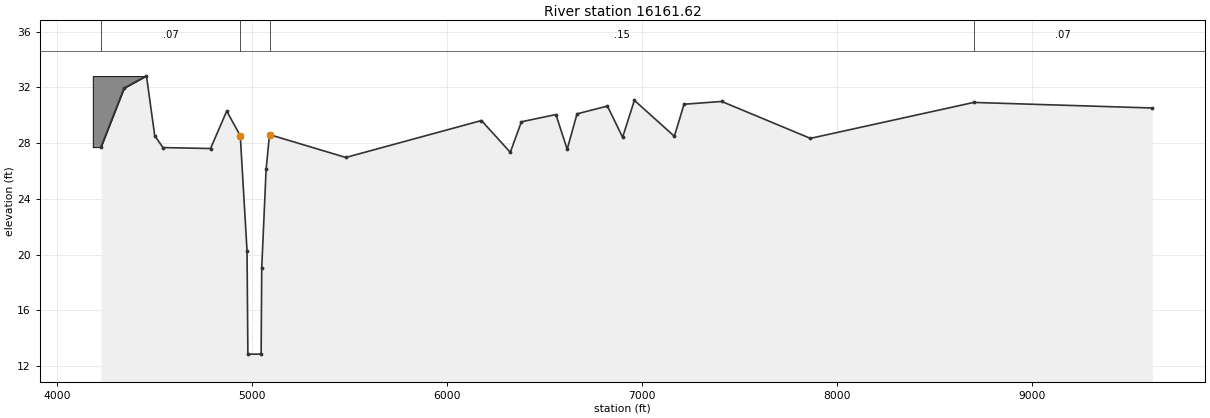
Type RM Length L Ch R = 1 ,16161.62,21.9,18.67,20
BEGIN DESCRIPTION:
Astoria Blvd
END DESCRIPTION:
XS GIS Cut Line= 6
      3178863.14    13782832.362     3178449.932    13782413.339
     3178253.623    13782223.816     3177352.249     13781298.82
     3175630.972    13779595.479     3175066.798    13778998.741
#Sta/Elev= 30
 4223.02   27.71 4341.78   31.95 4456.59   32.83 4499.02   28.53 4541.45   27.68
 4785.37   27.61 4868.44    30.3 4937.95   28.53 4972.64   20.28    4977   12.85
    5045   12.85 5048.09   19.04 5070.61   26.12 5087.96   28.61  5479.4   26.97
 6175.68   29.62 6323.51   27.34 6380.55   29.53 6557.61   30.05 6615.54   27.56
 6666.06    30.1 6822.03   30.66 6899.95   28.42 6960.39   31.07 7165.55   28.49
 7215.22   30.79 7408.38   30.99 7863.51   28.34 8701.48   30.92 9618.75   30.52
#Mann= 4 ,-1 , 0
 4223.02     .07       0 4937.95    .015       0 5087.96     .15       0
 8701.48     .07       0
#XS Ineff= 1 ,-1
    7000    8600    30.3
Permanent Ineff=
       F
#Block Obstruct= 1 ,-1
 4181.08 4455.43   32.81
Bank Sta=4937.95,5087.96
XS Rating Curve= 0 ,0
Exp/Cntr=0.5,0.3