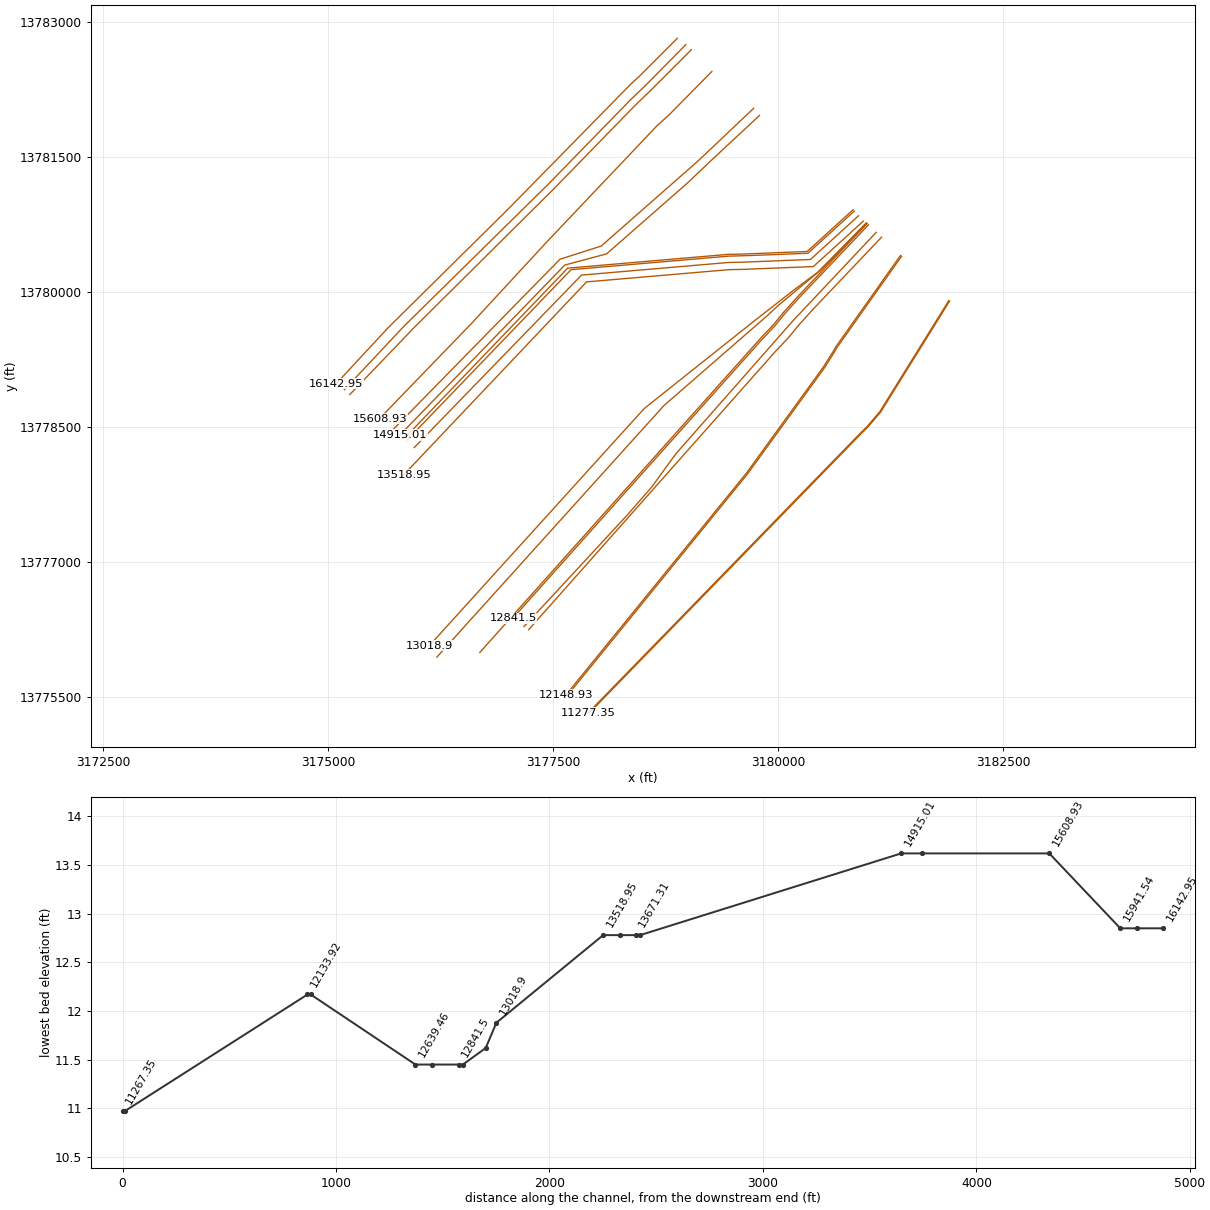
HEC-RAS study A119-00-00.prj: A119-00-00

--- A119-00-00.g01 (geometry) --- (continued)

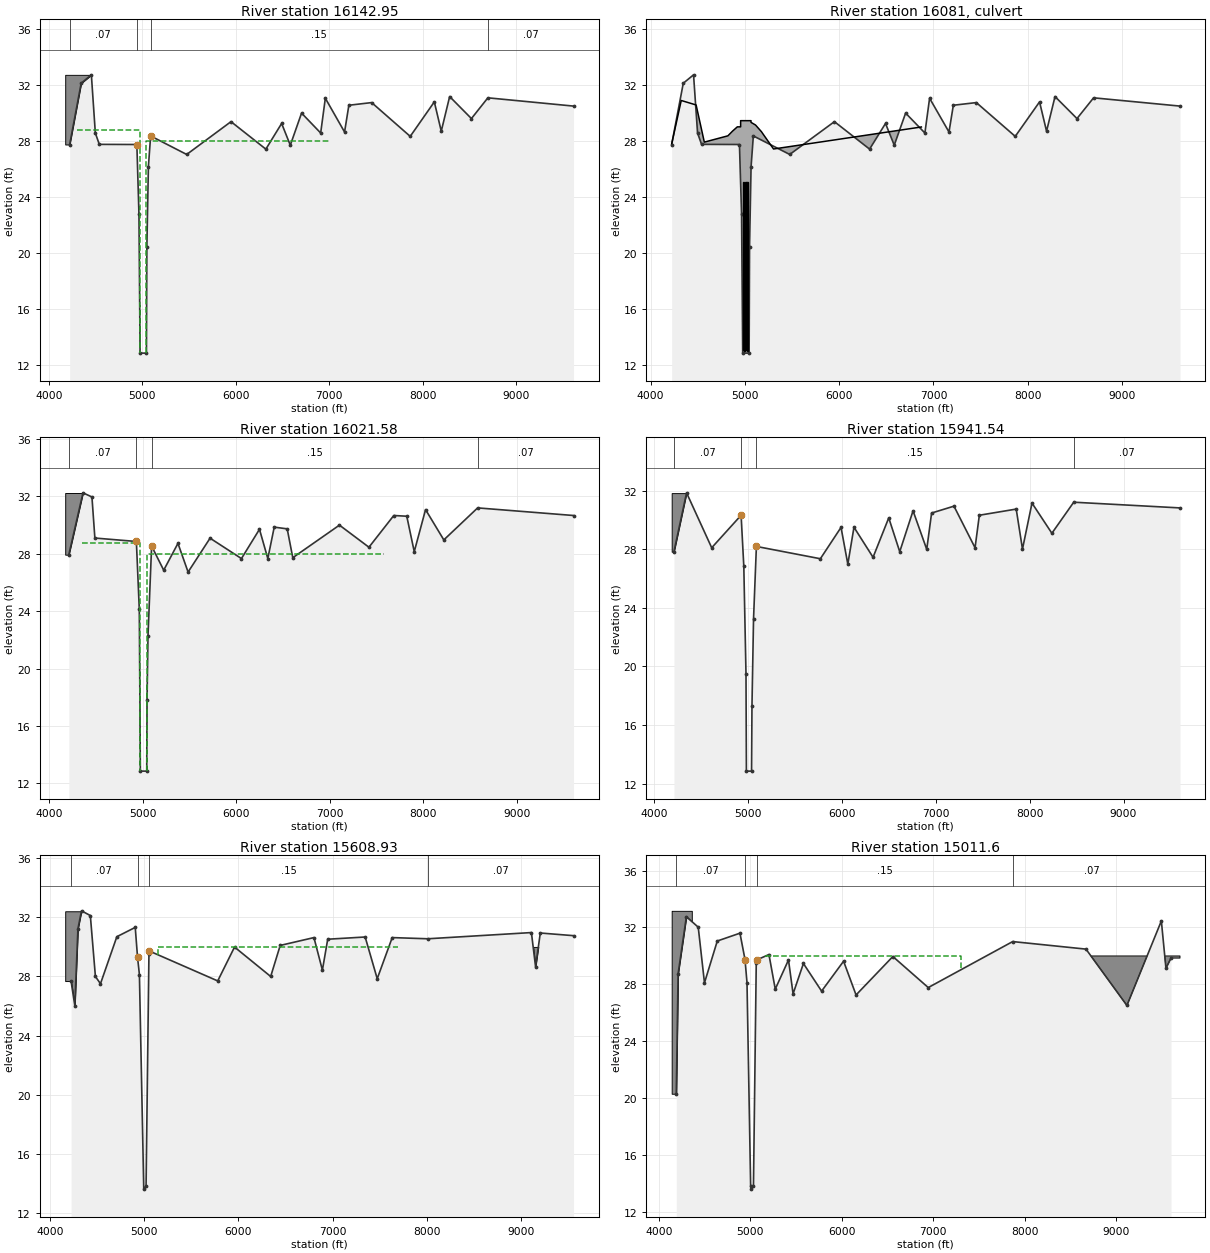
Type RM Length L Ch R = 1 ,16142.95,118.54,121.38,120.01
BEGIN DESCRIPTION:
Astoria Blvd
END DESCRIPTION:
XS GIS Cut Line= 6
      3178878.23    13782813.437     3178463.977    13782399.098
      3178360.45     13782303.83     3177011.415    13780928.958
     3175667.033     13779599.73     3175090.285    13778978.609
#Sta/Elev= 30
  4223.7   27.73  4346.7    32.1 4455.72    32.7 4498.14   28.55 4540.56   27.74
  4942.4   27.73 4964.96   22.75    4977   12.85    5045   12.85 5049.56   20.43
  5065.8   26.14 5089.86   28.34 5475.74   27.02 5949.68   29.36 6322.72    27.4
 6491.48   29.23 6584.22   27.68 6704.74   29.97 6909.24   28.55 6959.02   31.03
 7164.81   28.62 7210.78   30.53 7454.76   30.72 7867.36   28.31 8125.19   30.77
 8199.43   28.68 8289.19   31.15 8522.13   29.58  8698.2   31.06 9614.67   30.47
#Mann= 4 ,-1 , 0
  4223.7     .07       0  4942.4    .015       0 5089.86     .15       0
  8698.2     .07       0
#XS Ineff= 3 ,-1
    7000    8700      30    4300    4977   28.75    5043    6999      28
Permanent Ineff=
       F       F       F
#Block Obstruct= 1 ,-1
 4175.82 4455.11    32.7
Bank Sta=4942.4,5089.86
XS Rating Curve= 0 ,0
Exp/Cntr=0.5,0.3

Type RM Length L Ch R = 2 ,16081   ,,,
BEGIN DESCRIPTION:
Culverts at Astoria Blvd
END DESCRIPTION:
Bridge Culvert--1,0,-1,-1, 0
Deck Dist Width WeirC Skew NumUp NumDn MinLoCord MaxHiCord MaxSubmerge Is_Ogee
4,101,2.6,0, 15, 15, , , 0.95, 0, 0,0,,
    4225    4325    4483    4570    4820    4870    4920    4955    4955    5065
    5065    5113    5175    5304    6872
   27.81   30.87   30.55    27.9   28.35   28.69   28.99   28.99   29.43   29.43
   29.31   29.12   28.65   27.41   28.98
       0       0       0       0       0       0       0       0       0       0
       0       0       0       0       0
    4225    4325    4483    4570    4820    4870    4920    4955    4955    5065
    5065    5113    5175    5304    6872
   27.81   30.87   30.55    27.9   28.35   28.69   28.99   28.99   29.43   29.43
   29.31   29.12   28.65   27.41   28.98
       0       0       0       0       0       0       0       0       0       0
       0       0       0       0       0
Culvert=2,12,10,101,0.012,0.5,1,10,1,13.06,4988.5,12.99,4988.5,Culvert #1  , 0 ,4
Culvert Bottom n=0.012
Culvert=2,12,10,101,0.012,0.5,1,10,1,13.01,4999.5,13.01,4999.5,Culvert #2  , 0 ,4
Culvert Bottom n=0.012
Culvert=2,12,10,101,0.012,0.5,1,10,1,13.09,5010,12.99,5010,Culvert #3  , 0 ,4
Culvert Bottom n=0.012
Culvert=2,12,10,101,0.012,0.5,1,10,1,13.07,5020.5,12.88,5020.5,Culvert #4  , 0 ,4
Culvert Bottom n=0.012
Culvert=2,12,10,101,0.012,0.5,1,10,1,13.03,5031.5,12.94,5031.5,Culvert #5  , 0 ,4
Culvert Bottom n=0.012
BC Design=,, 0 ,, 0 ,,,,,,
BC HTab HWMax=32.7
BC Use User HTab Curves=0
BC User HTab FreeFlow(D)= 0

Type RM Length L Ch R = 1 ,16021.58,81.59,80.04,80.03
BEGIN DESCRIPTION:
Astoria Blvd
END DESCRIPTION:
XS GIS Cut Line= 6
      3178972.18     13782742.97     3178548.244    13782313.647
     3178352.605    13782124.791     3177451.725    13781200.302
     3175842.345    13779615.674     3175180.877    13778911.504
#Sta/Elev= 30
 4212.94   27.93 4364.32   32.24 4459.93   31.95 4491.19   29.09 4934.41   28.85
  4965.7   24.12    4977   12.85    5045   12.85 5048.43   17.83 5058.45   22.26
 5097.25   28.53 5226.46   26.85 5378.53   28.72 5486.81   26.72 5721.57   29.08
 6056.72   27.66 6249.31    29.7  6338.4   27.66 6406.82   29.85 6545.47   29.73
 6604.98   27.72 7103.51   29.99 7418.39   28.45 7683.94   30.66 7822.62   30.61
 7902.42   28.14 8023.18   31.07 8218.36   28.96 8579.51   31.19 9603.76   30.66
#Mann= 4 ,-1 , 0
 4212.94     .07       0 4934.41    .015       0 5097.25     .15       0
 8579.51     .07       0
#XS Ineff= 3 ,-1
    7700    8600      30    4350    4977   28.75    5043    7575      28
Permanent Ineff=
       F       F       F
#Block Obstruct= 1 ,-1
 4174.31 4363.84   32.23
Bank Sta=4934.41,5097.25
XS Rating Curve= 0 ,0
Exp/Cntr=0.5,0.3

Type RM Length L Ch R = 1 ,15941.54,334.52,332.61,344.22
BEGIN DESCRIPTION:
Astoria Blvd
END DESCRIPTION:
XS GIS Cut Line= 6
      3179034.82    13782688.162     3178604.422     13782256.68
     3178409.167    13782068.206     3177508.568    13781144.006
     3175963.015    13779609.032     3175241.272     13778857.82
#Sta/Elev= 30
 4210.18   27.83 4344.65   31.85 4612.39    28.1 4925.74   30.32  4954.5   26.83
 4977.77   19.48    4982   12.85    5037   12.85 5041.48   17.32 5058.16   23.26
 5088.59   28.19 5769.98   27.35 5990.22   29.49 6062.66   26.98 6128.12    29.5
 6331.46   27.45  6498.6   30.14  6615.6   27.83  6757.5   30.62 6903.34   27.99
 6955.04   30.47 7193.36   30.94 7418.05    28.1 7463.77   30.32 7856.56   30.74
 7923.25   28.01 8024.76   31.15 8236.54   29.09 8469.29   31.21 9601.46   30.82
#Mann= 4 ,-1 , 0
 4210.18     .07       0 4925.74    .015       0 5088.59     .15       0
 8469.29     .07       0
#XS Ineff= 1 ,-1
    7200    8500      30
Permanent Ineff=
       F
#Block Obstruct= 1 ,-1
 4185.99 4343.87   31.83
Bank Sta=4925.74,5088.59
XS Rating Curve= 0 ,0
Exp/Cntr=0.3,0.1

Type RM Length L Ch R = 1 ,15608.93,606.91,597.34,549.72
XS GIS Cut Line= 6
      3179261.88    13782445.441     3178778.484     13781955.37
     3178658.669    13781849.224     3177418.246    13780541.248
     3176594.899    13779649.447       3175572.6    13778591.813
#Sta/Elev= 30
 4223.63   27.69 4263.52   26.03  4296.5   31.22 4334.52   32.44 4428.26   32.12
 4482.08      28  4535.9   27.51 4709.83   30.69 4905.14   31.32 4929.52    29.3
 4949.36   28.13  4995.6   13.62 5020.07   13.82 5050.64   29.53 5055.45   29.72
 5780.99    27.7 5959.53   29.99 6343.39      28 6444.67    30.1 6802.82   30.63
 6892.59   28.43 6949.07   30.52  7346.7   30.67 7474.83   27.85 7633.99   30.63
 8012.09   30.55 9112.12   30.97 9156.31   28.66 9206.67   30.94 9559.48   30.76
#Mann= 4 ,-1 , 0
 4223.63     .07       0 4929.52    .015       0 5055.45     .15       0
 8012.09     .07       0
#XS Ineff= 2 ,-1
    4400    4800      30    5150    7700      30
Permanent Ineff=
       F       F
#Block Obstruct= 2 ,-1
  4161.4 4333.83   32.41 9056.93 9621.64      30
Bank Sta=4929.52,5055.45
XS Rating Curve= 0 ,0
Exp/Cntr=0.3,0.1

Type RM Length L Ch R = 1 ,15011.6 ,100.37,96.59,111.89
XS GIS Cut Line= 6
      3179725.32    13782035.953     3179174.266    13781513.937
      3179088.71    13781434.085     3178032.325    13780506.363
     3177575.796    13780360.803      3175722.11    13778469.482
#Sta/Elev= 30
 4191.29   20.32 4211.04   28.74 4301.56   32.76 4431.19   32.02 4499.41   28.11
 4639.53   31.05 4887.45    31.6  4942.6   29.75 4964.36   28.13 5004.22   13.86
  5010.6   13.62 5035.07   13.82 5065.64   29.53 5070.45   29.72 5204.48    30.1
 5273.39   27.67 5418.14   29.72 5468.29   27.34 5581.34   29.47 5780.01   27.53
 6020.53   29.63 6156.96   27.26 6559.35   29.96 6946.26   27.78  7869.7   31.01
 8671.12   30.48 9118.75   26.52  9495.3   32.46 9545.63   29.13 9600.72   29.85
#Mann= 4 ,-1 , 0
 4191.29     .07       0  4942.6    .015       0 5070.45     .15       0
  7869.7     .07       0
#XS Ineff= 2 ,-1
    4390    4875      31    5160    7300      30
Permanent Ineff=
       F       F
#Block Obstruct= 2 ,-1
 4140.74 4360.72   33.17  7912.7 9699.15      30
Bank Sta=4942.6,5070.45
XS Rating Curve= 0 ,0
Exp/Cntr=0.3,0.1

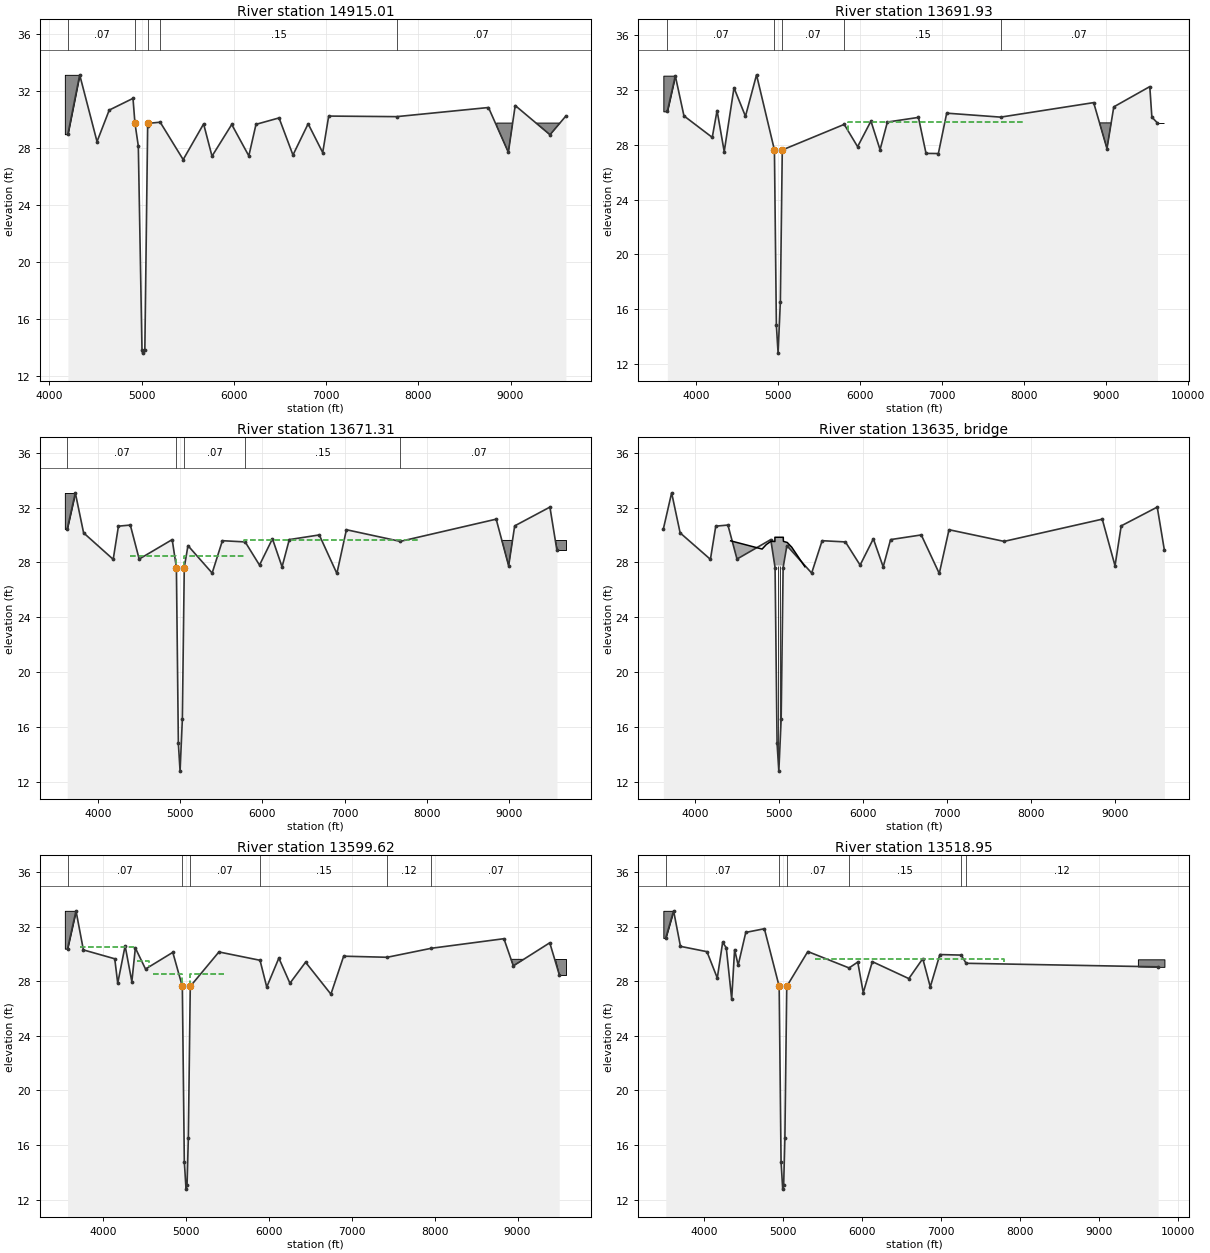
Type RM Length L Ch R = 1 ,14915.01,1501.32,1223.07,424.92
XS GIS Cut Line= 6
      3179790.47    13781957.088     3179239.584    13781443.626
     3178989.211     13781205.44     3178093.633    13780420.419
     3177629.584     13780296.12     3175798.236    13778408.581
#Sta/Elev= 30
 4200.81   28.96 4328.81   33.12 4516.75   28.44 4649.04   30.65 4906.77   31.47
  4927.6   29.75 4964.36   28.13 5004.22   13.86  5010.6   13.62 5035.07   13.82
 5065.64   29.53 5070.45   29.72 5201.59    29.8 5450.88   27.18 5672.33   29.68
 5763.27   27.42 5977.15   29.64 6162.61   27.44 6240.33   29.65 6490.18    30.1
 6641.15    27.5  6805.7   29.69 6963.76   27.67 7028.44   30.23 7764.77   30.19
 8761.01   30.83 8976.53   27.69 9050.74   30.97  9428.1   28.92 9600.75   30.24
#Mann= 5 ,-1 , 0
 4200.81     .07       0  4927.6    .015       0 5070.45     .07       0
 5201.59     .15       0 7764.77     .07       0
#XS Ineff= 2 ,-1
    4390    4800      31    5150    7700   29.75
Permanent Ineff=
       F       F
#Block Obstruct= 2 ,-1
 4167.79 4328.62   33.12 8850.49 9633.82   29.74
Bank Sta=4927.6,5070.45
XS Rating Curve= 0 ,0
Exp/Cntr=0.3,0.1

Type RM Length L Ch R = 1 ,13691.93,22.52,20.62,21.09
BEGIN DESCRIPTION:
Ryewater Drive
END DESCRIPTION:
XS GIS Cut Line= 6
      3180829.49    13780909.709     3180320.298    13780446.538
     3179598.554     13780417.75     3179443.735    13780414.773
      3177660.95    13780261.552     3175843.912    13778367.981
#Sta/Elev= 30
 3645.71   30.44 3742.88   33.04 3848.56   30.11 4193.66   28.54 4252.46    30.5
  4339.6    27.5 4458.92   32.16 4598.88   30.08 4733.76   33.11 4952.11   27.62
 4976.02    14.8  4996.8   12.78 5024.52   16.55 5047.89   27.62 5803.48   29.49
 5966.82   27.86 6129.52   29.73 6240.64   27.64 6330.12   29.66  6709.1      30
 6801.38   27.37 6951.82   27.36 7053.73   30.31 7711.58   30.02 8846.36   31.08
 9008.69   27.72 9091.92   30.77 9531.14   32.25 9556.48   30.02 9624.93   29.59
#Mann= 5 ,-1 , 0
 3645.71     .07       0 4952.11    .015       0 5047.89     .07       0
 5803.48     .15       0 7711.58     .07       0
#XS Ineff= 2 ,-1
 3780.43 4736.06      31    5850    8000   29.65
Permanent Ineff=
       F       F
#Block Obstruct= 2 ,-1
 3597.07 3743.05   33.05 8867.62 9709.67    29.6
Bank Sta=4952.11,5047.89
XS Rating Curve= 0 ,0
Exp/Cntr=0.5,0.3

Type RM Length L Ch R = 1 ,13671.31,78.82,71.69,73.82
BEGIN DESCRIPTION:
Ryewater Drive
END DESCRIPTION:
XS GIS Cut Line= 6
      3180842.95    13780894.914     3180328.367    13780426.841
     3179694.865    13780401.794     3179444.785    13780394.789
     3177698.391    13780244.696     3175875.939    13778350.623
#Sta/Elev= 30
 3622.98   30.43 3721.64   33.07 3822.66   30.15 4182.96   28.22 4246.64   30.64
 4391.18   30.72 4499.14   28.24 4900.96   29.66 4952.11   27.62 4976.02    14.8
  4996.8   12.78 5024.52   16.55 5047.89   27.62 5092.88   29.22 5387.42   27.22
    5512   29.58  5789.3   29.49 5963.72    27.8 6121.28   29.72  6238.3   27.67
 6326.28   29.66  6691.2      30  6905.6   27.19  7021.5   30.38 7676.54   29.53
 8844.52   31.15 8996.35   27.75 9069.78   30.66 9498.65   32.03 9584.09   28.87
#Mann= 5 ,-1 , 0
 3622.98     .07       0 4952.11    .015       0 5047.89     .07       0
  5789.3     .15       0 7676.54     .07       0
#XS Ineff= 4 ,-1
    3771 4390.86   30.64    4392    4950    28.5    5050    5780    28.5
    5781    7900   29.65
Permanent Ineff=
       F       F       F       F
#Block Obstruct= 2 ,-1
 3594.27  3721.2   33.06 8868.11 9693.52    29.6
Bank Sta=4952.11,5047.89
XS Rating Curve= 0 ,0
Exp/Cntr=0.5,0.3

Type RM Length L Ch R = 3 ,13635   ,,,
BEGIN DESCRIPTION:
Bridge at Ryewater Drive
END DESCRIPTION:
Bridge Culvert--1,0,-1,-1, 0
Deck Dist Width WeirC Skew NumUp NumDn MinLoCord MaxHiCord MaxSubmerge Is_Ogee
3,52,2.6,0, 14, 14, , , 0.95, 0, 0,0,,
    4424    4798    4848    4904    4950    4950    4956    5000    5050    5050
    5052    5097    5150    5307
   29.57   28.97    29.3   29.54   29.52   29.83   29.83   29.83   29.83   29.68
   29.53   29.45   29.11   27.68
       0       0       0       0       0   27.77   27.77   27.77   27.77       0
       0       0       0       0
    4424    4798    4848    4904    4950    4950    4956    5000    5050    5050
    5052    5097    5150    5307
   29.57   28.97    29.3   29.54   29.52   29.83   29.83   29.83   29.83   29.68
   29.53   29.45   29.11   27.68
       0       0       0       0       0   27.77   27.77   27.77   27.77       0
       0       0       0       0
Pier Skew, UpSta & Num, DnSta & Num=  ,4985, 4 ,4985, 4 , 3 , 3 , 0 ,,
    1.15    1.15       2       2
       0   25.77   25.77      28
    1.15    1.15       2       2
       0   25.77   25.77      28
Pier Skew, UpSta & Num, DnSta & Num=  ,5015, 4 ,5015, 4 , 3 , 3 , 0 ,,
    1.15    1.15       2       2
       0   25.77   25.77      28
    1.15    1.15       2       2
       0   25.77   25.77      28
BR Coef=-1 , 1 , 0 ,, 0 ,,,0.8,-1,2,0,
WSPro=,,,, 1 ,,,, 0 ,,,, 0 ,,,,-1 ,-1 ,-1 , 0 , 0 , 0 , 0 , 0
BC Design=,, 0 ,, 0 ,,,,,,
BC HTab HWMax=33.07
BC Use User HTab Curves=0
BC User HTab FreeFlow(D)= 0

Type RM Length L Ch R = 1 ,13599.62,90.07,80.68,84.37
BEGIN DESCRIPTION:
Ryewater Drive
END DESCRIPTION:
XS GIS Cut Line= 6
      3180890.05    13780843.131     3180356.608    13780357.903
     3179601.316    13780327.786     3179448.459    13780324.847
     3177814.727    13780184.437     3175957.242     13778269.32
#Sta/Elev= 30
 3566.07   30.38 3668.04   33.15 3757.16   30.29 4135.92   29.64 4171.82   27.85
 4261.18   30.59  4342.4   27.96 4384.64   30.43 4507.52   28.89 4836.86   30.11
 4952.11   27.62 4976.02    14.8  4996.8   12.78 5009.08    13.1 5024.52   16.55
 5047.89   27.62 5393.98   30.14 5890.26   29.53 5971.44   27.57 6117.56   29.69
 6251.44   27.85 6440.32   29.39 6746.32   27.05 6900.19   29.83 7425.51   29.75
 7959.89   30.41 8835.57   31.11 8949.12   29.12 9389.14   30.81 9503.67   28.48
#Mann= 6 ,-1 , 0
 3566.07     .07       0 4952.11    .015       0 5047.89     .07       0
 5890.26     .15       0 7425.51     .12       0 7959.89     .07       0
#XS Ineff= 5 ,-1
 3714.79 4384.04    30.5    4600    4950    28.5    5050    5450    28.5
    4400    4550    29.5    5451    7850    29.5
Permanent Ineff=
       F       F       F       F       F
#Block Obstruct= 2 ,-1
 3533.27 3667.27   33.15 8893.09 9584.35    29.6
Bank Sta=4952.11,5047.89
XS Rating Curve= 0 ,0
Exp/Cntr=0.5,0.3

Type RM Length L Ch R = 1 ,13518.95,89.41,500.05,1112.06
BEGIN DESCRIPTION:
Ryewater Drive
END DESCRIPTION:
XS GIS Cut Line= 6
      3180943.88    13780783.951     3180388.884    13780279.117
     3179603.771    13780247.819     3179452.658    13780244.913
     3177870.746    13780108.956     3175841.094    13777967.335
#Sta/Elev= 30
 3518.34   31.16  3617.4   33.15 3704.03   30.55 4039.12   30.16 4169.83   28.23
 4237.71   30.85 4283.61   30.44 4351.69   26.69 4388.69   30.31 4433.73   29.17
 4529.94   31.57 4765.03   31.84 4952.11   27.62 4976.02    14.8  4996.8   12.78
 5009.08    13.1 5024.52   16.55 5047.89   27.62 5314.32   30.17 5835.86   28.97
 5945.65    29.4 6015.39   27.16 6130.02   29.43 6591.48   28.19 6767.77   29.65
 6862.66   27.58 6983.72   29.95 7253.63   29.91 7315.88   29.31 9743.82   29.05
#Mann= 6 ,-1 , 0
 3518.34     .07       0 4952.11    .015       0 5047.89     .07       0
 5835.86     .15       0 7253.63     .07       0 7315.88     .12       0
#XS Ineff= 2 ,-1
 3621.16 4544.94    30.5    5400    7800    29.6
Permanent Ineff=
       F       F
#Block Obstruct= 2 ,-1
 3487.74    3617   33.15  9487.5 9822.95    29.6
Bank Sta=4952.11,5047.89
XS Rating Curve= 0 ,0
Exp/Cntr=0.3,0.1

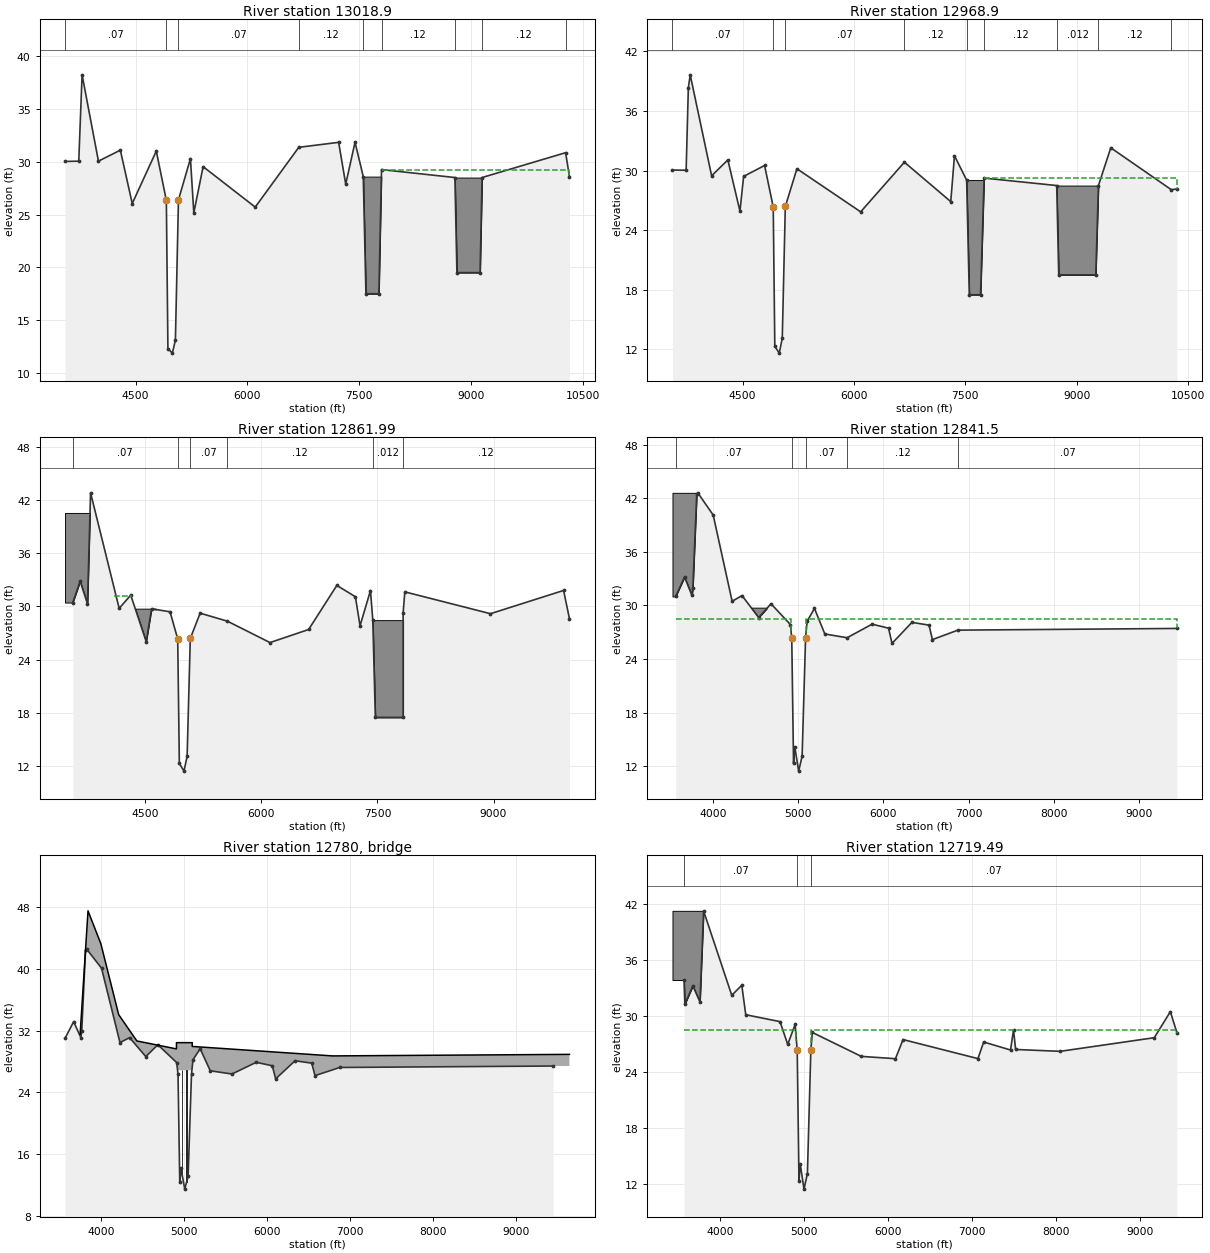
Type RM Length L Ch R = 1 ,13018.9 ,25.52,50,317.37
BEGIN DESCRIPTION:
Added cross-section is interpolated in channel banks and uses 2001 LiDAR in the overbanks and survey in the project boundary
Watearth, 2018
END DESCRIPTION:
XS GIS Cut Line= 6
 3180975.959577613780763.0775837 3180437.875451113780215.7620929
 3180173.599818313780019.6633645 3179719.187528813779664.5657316
 3178511.116944913778703.2600368 3176125.7665147 13776070.652071
#Sta/Elev= 30
 3552.38   30.02 3736.78   30.05 3781.64   38.22 4000.93   30.05 4294.98   31.09
 4454.53   26.04 4777.35      31  4912.3   26.34 4933.46   12.31  4993.4   11.88
 5033.94   13.12 5074.92   26.39 5235.84   30.29 5280.81   25.15 5405.72   29.53
 6105.21    25.7 6689.78   31.36  7224.7   31.83  7319.7   27.87 7444.69   31.84
    7555   28.59 7590.81    17.5 7764.75    17.5    7800   29.25    8785    28.5
    8812    19.5    9123    19.5    9150    28.510270.75   30.8510322.26   28.59
#Mann= 9 ,-1 , 0
 3552.38     .07       0  4912.3    .015       0 5074.92     .07       0
 6689.78     .12       0    7555    .012       0    7800     .12       0
    8785    .012       0    9150     .12       010270.75     .07       0
#XS Ineff= 2 , 0
       0                    7800       0   29.25
Permanent Ineff=
       F       T
#Block Obstruct= 2 ,-1
    7555    7800   28.59    8785    9150    28.5
Bank Sta=4912.3,5074.92
XS Rating Curve= 0 ,0
Exp/Cntr=0.3,0.1

Type RM Length L Ch R = 1 ,12968.9 ,17.39,106.91,216.28
BEGIN DESCRIPTION:
Added cross-section is interpolated in channel banks and uses 2001 LiDAR in the overbanks and survey in the project boundary
Watearth, 2018
END DESCRIPTION:
XS GIS Cut Line= 6
  3180979.16700113780760.9905898 3180479.514130213780248.0903548
 3179996.729097313779845.2121239 3179882.952173413779738.8971702
 3178730.283610413778736.3001258 3176207.777386113775942.0164816
#Sta/Elev= 30
 3555.79   30.06 3739.77   30.04 3769.61   38.35 3794.47   39.65 4082.88   29.48
 4301.47   31.08 4464.49   25.92 4513.89   29.42 4796.27   30.52 4912.71   26.34
 4933.87   12.31 4993.81   11.62 5034.35   13.12 5075.33   26.39 5231.73   30.19
 6090.03   25.85 6679.04   30.85 7303.27   26.88 7353.21    31.5    7517   29.05
 7552.81    17.5 7704.47    17.5 7752.46   29.25    8730    28.5 8757.05    19.5
    9256    19.5    9292    28.5 9457.99    32.310273.53   28.08 10348.6   28.16
#Mann= 9 ,-1 , 0
 3555.79     .07       0 4912.71    .015       0 5075.33     .07       0
 6679.04     .12       0    7517    .012       0 7752.46     .12       0
    8730    .012       0    9292     .12       010273.53     .07       0
#XS Ineff= 2 , 0
       0                 7752.46       0   29.25
Permanent Ineff=
       F       T
#Block Obstruct= 2 ,-1
    7517 7752.46   29.05    8730    9292    28.5
Bank Sta=4912.71,5075.33
XS Rating Curve= 0 ,0
Exp/Cntr=0.3,0.1

Type RM Length L Ch R = 1 ,12861.99,23.46,20.49,20.23
BEGIN DESCRIPTION:
Dixie Farm Road
END DESCRIPTION:
XS GIS Cut Line= 6
      3180986.03    13780756.525     3180212.405    13779942.422
     3180054.062    13779766.104     3179951.523    13779640.191
     3179802.986    13779482.528 3176685.203422213775994.0439423
#Sta/Elev= 30
 3563.07 30.43433657.906 32.84263752.742 30.28683792.673 42.79344162.034 29.7841
4311.775 31.2691 4511.43 26.03554581.309 29.73314819.431 29.3932 4918.69   26.34
 4939.85   12.31 4999.79   11.45 5040.33   13.12 5081.31   26.395208.568 29.2396
5561.795 28.33466111.139 25.92756610.542 27.40086975.106 32.3665 7214.82 31.0888
7274.749 27.82187409.587 31.7866 7439.54 28.45547472.406    17.57831.415    17.5
7831.435   29.257853.396 31.6406 8960.03   29.18 9905.07 31.79939980.79428.61994
#Mann= 6 ,-1 , 0
 3563.07     .07       0 4918.69    .015       0 5081.31     .07       0
5561.795     .12       0 7439.54    .012       07831.435     .12       0
#XS Ineff= 1 ,-1
 4092.84 4318.79   31.13
Permanent Ineff=
       F
#Block Obstruct= 3 ,-1
 3462.38 3820.91   40.53 4096.74  4636.3   29.75 7439.54 7831.44 28.4554
Bank Sta=4918.69,5081.31
XS Rating Curve= 0 ,0
Exp/Cntr=0.5,0.3

Type RM Length L Ch R = 1 ,12841.5 ,137.38,122.01,125.78
BEGIN DESCRIPTION:
Dixie Farm Road
END DESCRIPTION:
XS GIS Cut Line= 6
      3181000.53    13780742.748     3180227.097    13779928.849
     3180069.265      13779753.1     3179966.575    13779627.002
     3179817.723    13779469.004     3177053.142    13776375.862
#Sta/Elev= 30
 3560.57      31 3664.54   33.17  3751.5   31.11  3762.2   31.95 3807.84   42.45
 3820.36    42.6 4001.02   40.11 4223.52   30.46 4339.44    31.1  4535.4   28.64
 4680.06   30.18 4907.75   27.86 4923.69   26.34 4944.85   12.31 4959.51   14.16
 5004.79   11.45 5045.33   13.12 5086.31   26.39 5104.36   28.23 5190.73   29.66
 5312.42    26.8 5574.02   26.38 5867.26    27.9 6060.62   27.45 6101.34   25.75
 6335.54    28.1 6536.72   27.79 6575.62   26.17 6874.96   27.23 9447.81   27.42
#Mann= 5 ,-1 , 0
 3560.57     .07       0 4923.69    .015       0 5086.31     .07       0
 5574.02     .12       0 6874.96     .07       0
#XS Ineff= 2 , 0
       0    4915    28.5    5093       0    28.5
Permanent Ineff=
       F       F
#Block Obstruct= 2 ,-1
  3522.7 3819.65    42.6 4374.81 4629.06   29.75
Bank Sta=4923.69,5086.31
XS Rating Curve= 0 ,0
Exp/Cntr=0.5,0.3

Type RM Length L Ch R = 3 ,12780   ,,,
BEGIN DESCRIPTION:
Bridge at Dixie Farm Road
END DESCRIPTION:
Bridge Culvert--1,0,-1,-1, 0
Deck Dist Width WeirC Skew NumUp NumDn MinLoCord MaxHiCord MaxSubmerge Is_Ogee
8,70,2.6,0, 11, 11, , , 0.95, 0, 0,0,,
    3743    3838    3993    4208    4427    4905    4905    5095    5095    6787
    9645
   31.56   47.55   43.28   34.08   30.67   29.64   30.45   30.45   29.96   28.73
   28.93
       0       0       0       0       0       0   26.87   26.87       0       0
       0
    3743    3838    3993    4208    4427    4905    4905    5095    5095    6787
    9645
   31.56   47.55   43.28   34.08   30.67   29.64   30.45   30.45   29.96   28.73
   28.93
       0       0       0       0       0       0   26.87   26.87       0       0
       0
Pier Skew, UpSta & Num, DnSta & Num=  ,4973, 4 ,4973, 4 , 3 , 3 , 0 ,,
    1.35    1.35    2.75    2.75
       0   24.12   24.12      27
    1.35    1.35    2.75    2.75
       0   24.12   24.12      27
Pier Skew, UpSta & Num, DnSta & Num=  ,5027, 4 ,5027, 4 , 3 , 3 , 0 ,,
    1.35    1.35    2.75    2.75
       0   24.12   24.12      27
    1.35    1.35    2.75    2.75
       0   24.12   24.12      27
BR Coef=-1 , 1 , 0 ,, 0 ,,,0.8,-1,2,0,
WSPro=,,,, 1 ,,,, 0 ,,,, 0 ,,,,-1 ,-1 ,-1 , 0 , 0 , 0 , 0 , 0
BC Design=,, 0 ,, 0 ,,,,,,
BC HTab HWMax=42.6
BC Use User HTab Curves=0
BC User HTab FreeFlow(D)= 0

Type RM Length L Ch R = 1 ,12719.49,82.03,80.03,78.7
BEGIN DESCRIPTION:
Dixie Farm Road
END DESCRIPTION:
XS GIS Cut Line= 6
      3181087.52    13780660.085     3180160.483    13779675.077
     3178861.536    13778199.463     3178595.745    13777832.907
     3178310.205    13777506.576     3177175.897    13776281.795
#Sta/Elev= 30
  3569.2   33.85 3578.98   31.25 3674.47   33.22 3759.35    31.5 3802.92   41.24
 4138.55   32.21 4257.87   33.29 4305.34   30.13 4713.78   29.39 4805.67   26.95
    4894    29.1 4918.69   26.34 4939.85   12.31 4954.51   14.16 4999.79   11.45
 5040.33   13.12 5081.31   26.39 5099.36   28.23 5682.28   25.67 6089.81   25.42
 6180.46   27.47 7073.21   25.43 7141.65   27.21 7461.64   26.35 7497.41   28.51
 7522.44   26.41  8053.9   26.21 9175.42   27.67 9367.14   30.46 9445.16   28.21
#Mann= 3 ,-1 , 0
  3569.2     .07       0 4918.69    .015       0 5081.31     .07       0
#XS Ineff= 2 , 0
       0    4910    28.5    5088       0    28.5
Permanent Ineff=
       F       F
#Block Obstruct= 1 ,-1
 3431.66 3800.16   41.26
Bank Sta=4918.69,5081.31
XS Rating Curve= 0 ,0
Exp/Cntr=0.5,0.3

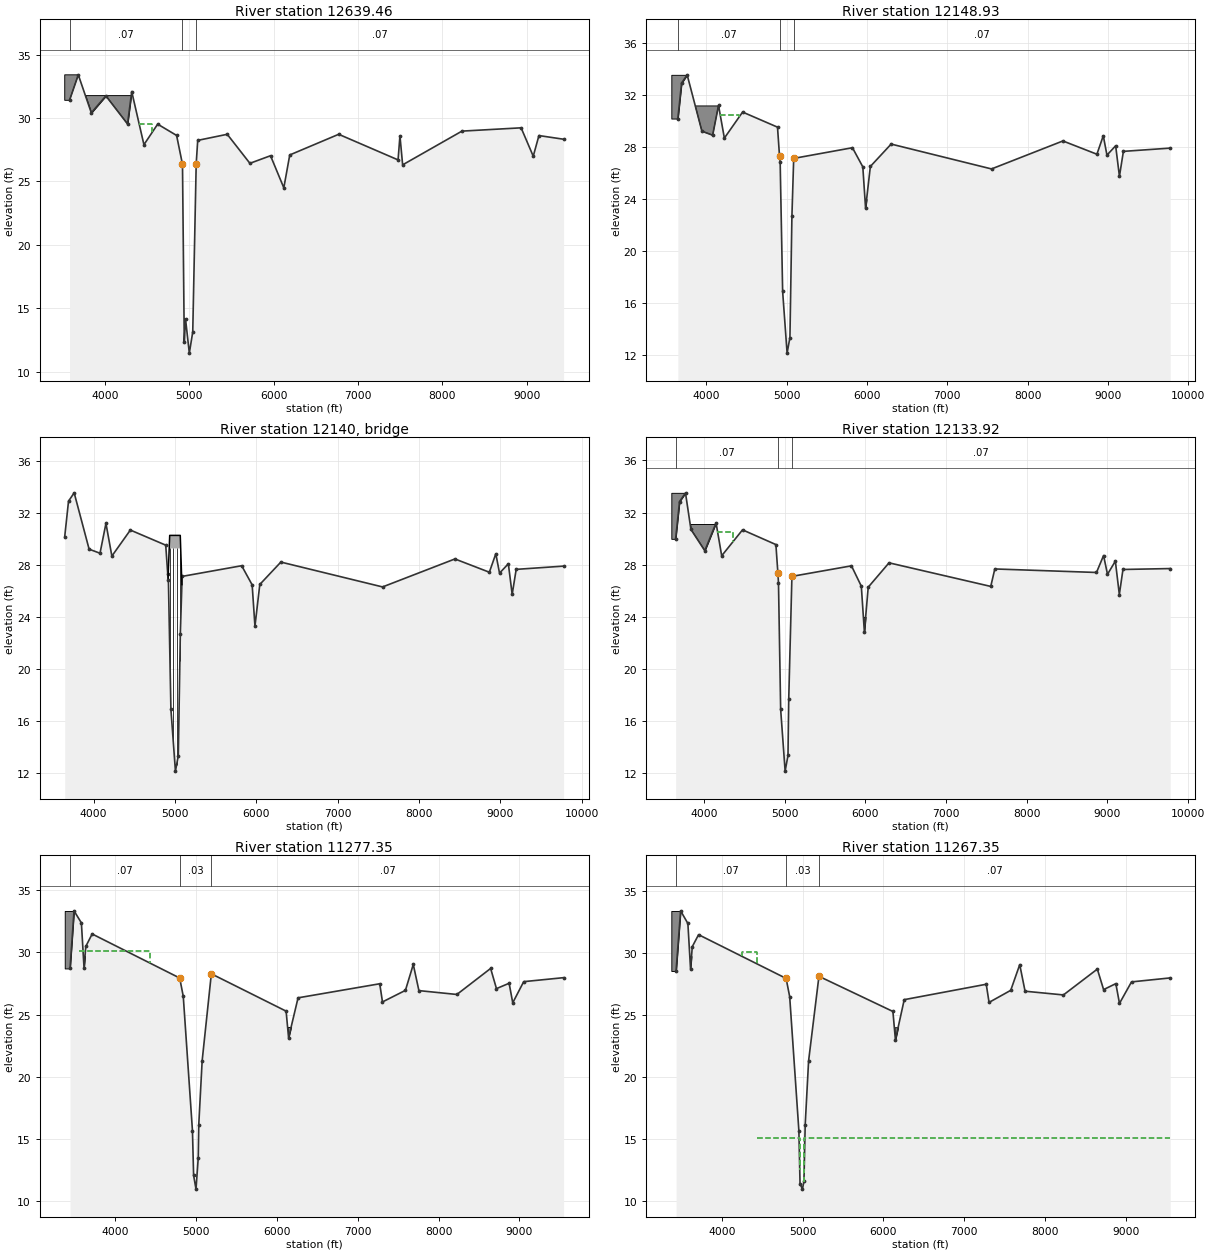
Type RM Length L Ch R = 1 ,12639.46,416.4,490.53,601.75
BEGIN DESCRIPTION:
Dixie Farm Road
END DESCRIPTION:
XS GIS Cut Line= 6
      3181145.51    13780604.976     3180374.017     13779793.12
     3180221.296    13779623.061     3180117.097    13779495.111
     3179965.095    13779333.769     3177228.583    13776247.774
#Sta/Elev= 30
 3579.01   31.39 3683.02    33.4 3837.34    30.4 4010.12   31.74 4267.18   29.52
 4316.46   32.08 4461.42   27.89  4624.3   29.51 4848.91   28.62 4918.69   26.34
 4939.85   12.31 4954.51   14.16 4999.79   11.45 5040.33   13.12 5081.31   26.39
 5099.36   28.23 5449.44   28.71 5718.26   26.42 5962.74   27.02 6120.42   24.49
  6190.8   27.08 6771.26   28.71  7475.4   26.69 7497.76   28.59 7529.64    26.3
 8232.98   28.96 8934.72   29.22 9078.74   26.98 9146.06   28.61 9438.76   28.32
#Mann= 3 ,-1 , 0
 3579.01     .07       0 4918.69     .03       0 5081.31     .07       0
#XS Ineff= 1 ,-1
    4400    4560    29.5
Permanent Ineff=
       F
#Block Obstruct= 3 ,-1
 3522.12 3683.46    33.4 3726.16 4315.45    31.8 5970.42 6241.18      24
Bank Sta=4918.69,5081.31
XS Rating Curve= 0 ,0
Exp/Cntr=0.3,0.1

Type RM Length L Ch R = 1 ,12148.93,15.56,15.01,15.44
BEGIN DESCRIPTION:
Pipe
END DESCRIPTION:
XS GIS Cut Line= 6
       3181355.9    13780401.899     3180636.389    13779385.689
     3180607.489    13779334.047     3180496.544    13779158.394
     3179643.004    13777981.895     3177645.056    13775527.302
#Sta/Elev= 30
 3645.16   30.19 3691.71   32.91 3761.08   33.55 3944.78   29.22 4078.61   28.91
 4151.67    31.2 4224.38   28.69 4451.58   30.69 4886.12   29.53 4911.11   27.31
 4919.12   26.85    4950   16.91 5005.51   12.17 5040.84   13.37 5065.55   22.71
 5087.75   27.13 5819.34   27.95 5948.28   26.48 5982.72    23.3 6042.23   26.51
 6301.16   28.23 7550.85   26.32 8439.94   28.47 8863.08   27.45 8942.56   28.87
 8988.31   27.38 9096.58    28.1 9143.65   25.75 9192.97   27.67 9775.68   27.92
#Mann= 3 ,-1 , 0
 3645.16     .07       0 4911.11     .03       0 5087.75     .07       0
#XS Ineff= 3 ,-1
    4408 4911.11   27.31 4172.21 4407.77   30.43 5087.75 9775.68   27.13
Permanent Ineff=
       F       F       F
#Block Obstruct= 3 ,-1
 3563.88 3759.44   33.55 3768.01 4157.28   31.16    5843 6145.62      24
Bank Sta=4911.11,5087.75
XS Rating Curve= 0 ,0
Exp/Cntr=0.3,0.1

Type RM Length L Ch R = 3 ,12140   ,,,
BEGIN DESCRIPTION:
Pipe Crossing downstream of Dixie Farm Road
END DESCRIPTION:
Bridge Culvert--1,0,-1,-1, 0
Deck Dist Width WeirC Skew NumUp NumDn MinLoCord MaxHiCord MaxSubmerge Is_Ogee
4,5,2.6,0, 4, 4, , , 0.95, 0, 0,0,,
    4915    4935    5065    5085
      27   30.28   30.28    26.5
      26   29.28   29.28    25.5
    4915    4935    5065    5085
      27   30.28   30.28    26.5
      26   29.28   29.28    25.5
Pier Skew, UpSta & Num, DnSta & Num=  ,4940, 4 ,4940, 4 , 3 , 3 , 0 ,,
    1.15    1.15       2       2
       0   27.28   27.28      30
    1.15    1.15       2       2
       0   27.28   27.28      30
Pier Skew, UpSta & Num, DnSta & Num=  ,4980, 4 ,4980, 4 , 3 , 3 , 0 ,,
    1.15    1.15       2       2
       0   27.28   27.28      30
    1.15    1.15       2       2
       0   27.28   27.28      30
Pier Skew, UpSta & Num, DnSta & Num=  ,5020, 4 ,5020, 4 , 3 , 3 , 0 ,,
    1.15    1.15       2       2
       0   27.28   27.28      30
    1.15    1.15       2       2
       0   27.28   27.28      30
Pier Skew, UpSta & Num, DnSta & Num=  ,5060, 4 ,5060, 4 , 3 , 3 , 0 ,,
    1.15    1.15       2       2
       0   27.28   27.28      30
    1.15    1.15       2       2
       0   27.28   27.28      30
BR Coef=-1 , 1 , 0 ,, 0 ,,,0.8,-1,2,0,
WSPro=,,,, 1 ,,,, 0 ,,,, 0 ,,,,-1 ,-1 ,-1 , 0 , 0 , 0 , 0 , 0
BC Design=,, 0 ,, 0 ,,,,,,
BC HTab HWMax=33.55
BC Use User HTab Curves=0
BC User HTab FreeFlow(D)= 0

Type RM Length L Ch R = 1 ,12133.92,783.2,856.57,758.1
BEGIN DESCRIPTION:
Pipe
END DESCRIPTION:
XS GIS Cut Line= 6
      3181368.14    13780393.231     3180649.091     13779377.67
     3180620.391    13779326.387     3180508.961    13779149.965
     3179654.904    13777972.755     3177658.226    13775517.257
#Sta/Elev= 30
 3648.12   29.99 3696.59   32.85 3770.37   33.51 3837.77   30.71 4009.58   29.08
 4149.44   31.21 4218.99   28.69  4477.4   30.68 4891.01   29.55 4915.77   27.36
  4923.1   26.61    4950   16.91 5005.51   12.17 5040.84   13.37    5050   17.67
 5089.64   27.11 5827.87   27.92 5949.91   26.36  5987.9   22.86 6035.52   26.28
 6293.55   28.15 7554.56   26.34 7604.89   27.68 8865.52   27.41 8953.17   28.71
  9001.9   27.27 9099.26   28.28 9148.63   25.72 9193.65   27.64 9779.13   27.71
#Mann= 3 ,-1 , 0
 3648.12     .07       0 4915.77     .03       0 5089.64     .07       0
#XS Ineff= 3 ,-1
    4356 4915.77   27.36 4164.23 4355.23    30.5 5089.64 9779.13   27.11
Permanent Ineff=
       F       F       F
#Block Obstruct= 3 ,-1
 3594.59 3770.59   33.52 3780.32 4151.45   31.13 5866.89 6169.51      24
Bank Sta=4915.77,5089.64
XS Rating Curve= 0 ,0
Exp/Cntr=0.3,0.1

Type RM Length L Ch R = 1 ,11277.35,10.27,10,12.95
BEGIN DESCRIPTION:
access road
END DESCRIPTION:
XS GIS Cut Line= 5
       3181893.6    13779902.011     3181126.859    13778667.748
     3180984.568    13778501.444     3180920.084    13778438.803
     3177890.011    13775324.954
#Sta/Elev= 30
 3439.76    28.7 3489.05   33.33  3580.2   32.36 3612.87   28.76 3634.66   30.47
 3713.38   31.47 4796.46   27.93 4840.61   26.46 4954.32   15.67 4968.63   12.07
 4998.17   10.97 5026.06    13.5  5032.5   16.16 5074.39   21.29 5187.96   28.27
 6113.06   25.27 6143.62   23.13 6260.94   26.34 7271.38   27.47 7305.37   26.01
 7589.29   26.94 7686.42   29.02 7756.05   26.92 8225.92   26.61 8643.39    28.7
 8715.62   27.08 8872.32   27.51 8917.04   25.94 9052.72   27.64 9546.37   27.96
#Mann= 3 ,-1 , 0
 3439.76     .07       0 4796.46     .03       0 5187.96     .07       0
#XS Ineff= 1 ,-1
 3552.26 4430.19    30.1
Permanent Ineff=
       F
#Block Obstruct= 3 ,-1
 3374.08 3488.52   33.32 3576.75 3637.63    29.7 6097.84 6265.07      24
Bank Sta=4796.46,5187.96
XS Rating Curve= 0 ,0
Exp/Cntr=0.5,0.3

Type RM Length L Ch R = 1 ,11267.35,51.35,50.03,65.33
BEGIN DESCRIPTION:
access road
END DESCRIPTION:
XS GIS Cut Line= 5
      3181902.09    13779896.734     3181134.952    13778661.825
     3180991.866    13778494.593     3180927.152    13778431.729
     3177896.965    13775317.761
#Sta/Elev= 30
 3436.08   28.53 3492.11   33.37 3582.05   32.35 3614.73   28.71 3636.51   30.49
  3714.3   31.45 4796.46   27.93 4840.61   26.46 4954.32   15.67 4968.63    11.4
 4998.17   10.97 5017.01    11.6  5032.5   16.16 5074.39   21.29 5202.44    28.1
 6116.88   25.27 6147.95   22.99 6256.81   26.22  7270.8   27.46 7305.64      26
 7573.53   26.97 7684.92   29.04 7750.79    26.9 8225.11    26.6  8644.3   28.68
 8721.75   27.03 8873.03   27.51 8918.19   25.92 9066.97   27.65 9545.16   27.97
#Mann= 3 ,-1 , 0
 3436.08     .07       0 4796.46     .03       0 5202.44     .07       0
#XS Ineff= 4 ,-1
    4441    4965    15.1  3512.2 3728.46   30.66    5015 9545.16    15.1
    4250    4440   30.05
Permanent Ineff=
       F       F       F       F
#Block Obstruct= 3 ,-1
  3377.2 3491.25   33.36 3582.16 3641.54   29.72 6097.84 6312.86      24
Bank Sta=4796.46,5202.44
XS Rating Curve= 0 ,0
Exp/Cntr=0.5,0.3