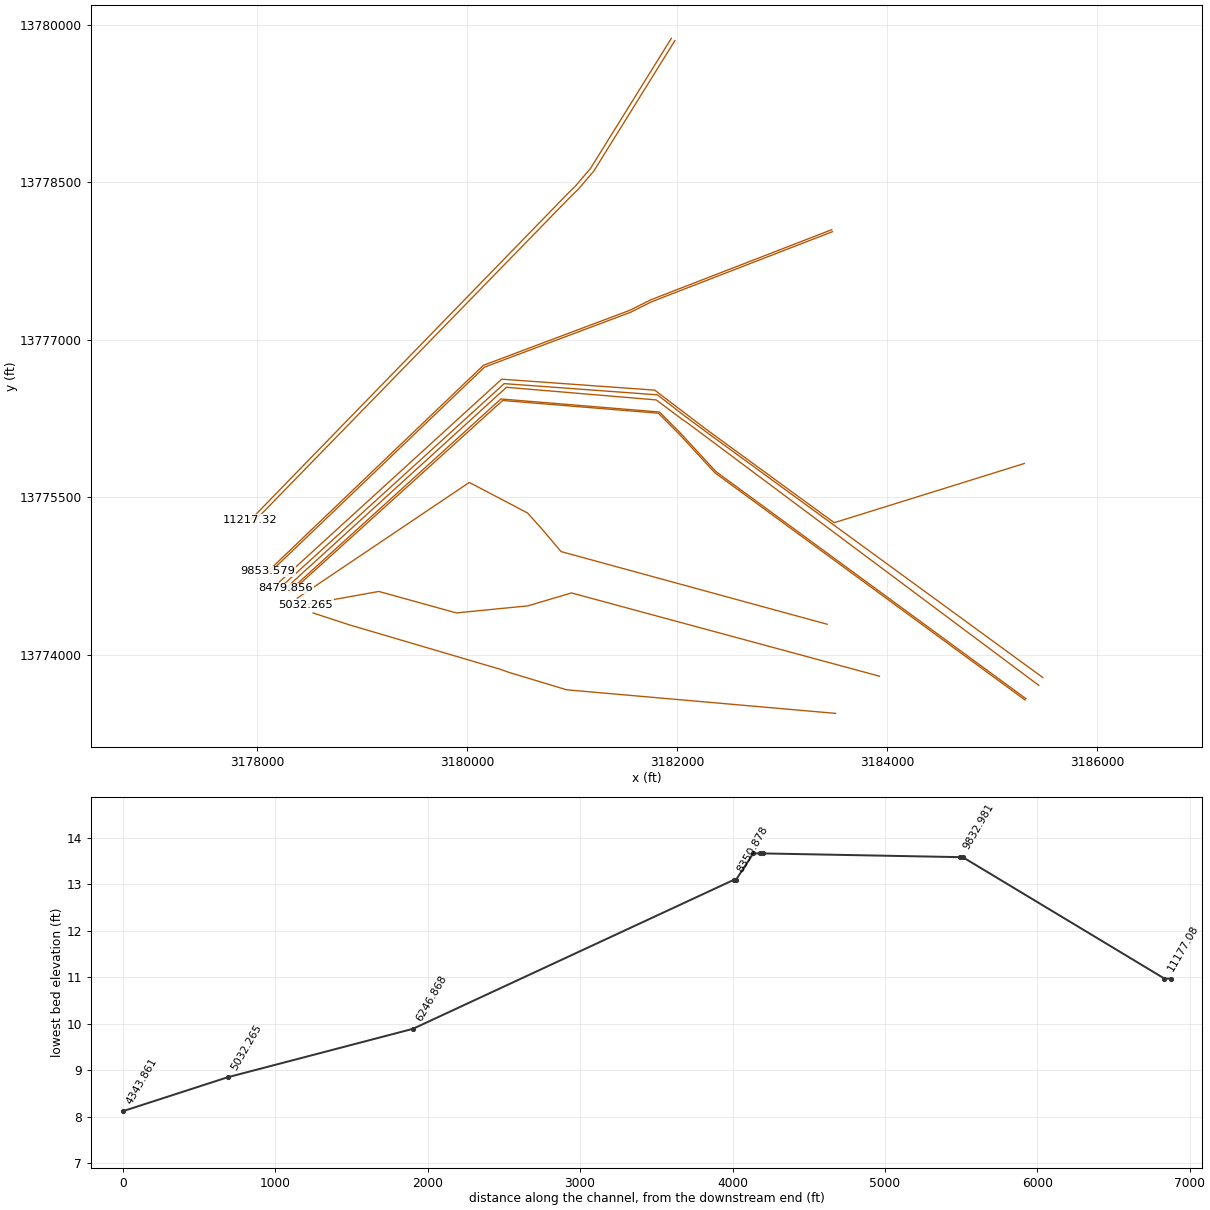
HEC-RAS study A119-00-00.prj: A119-00-00

--- A119-00-00.g01 (geometry) --- (continued)

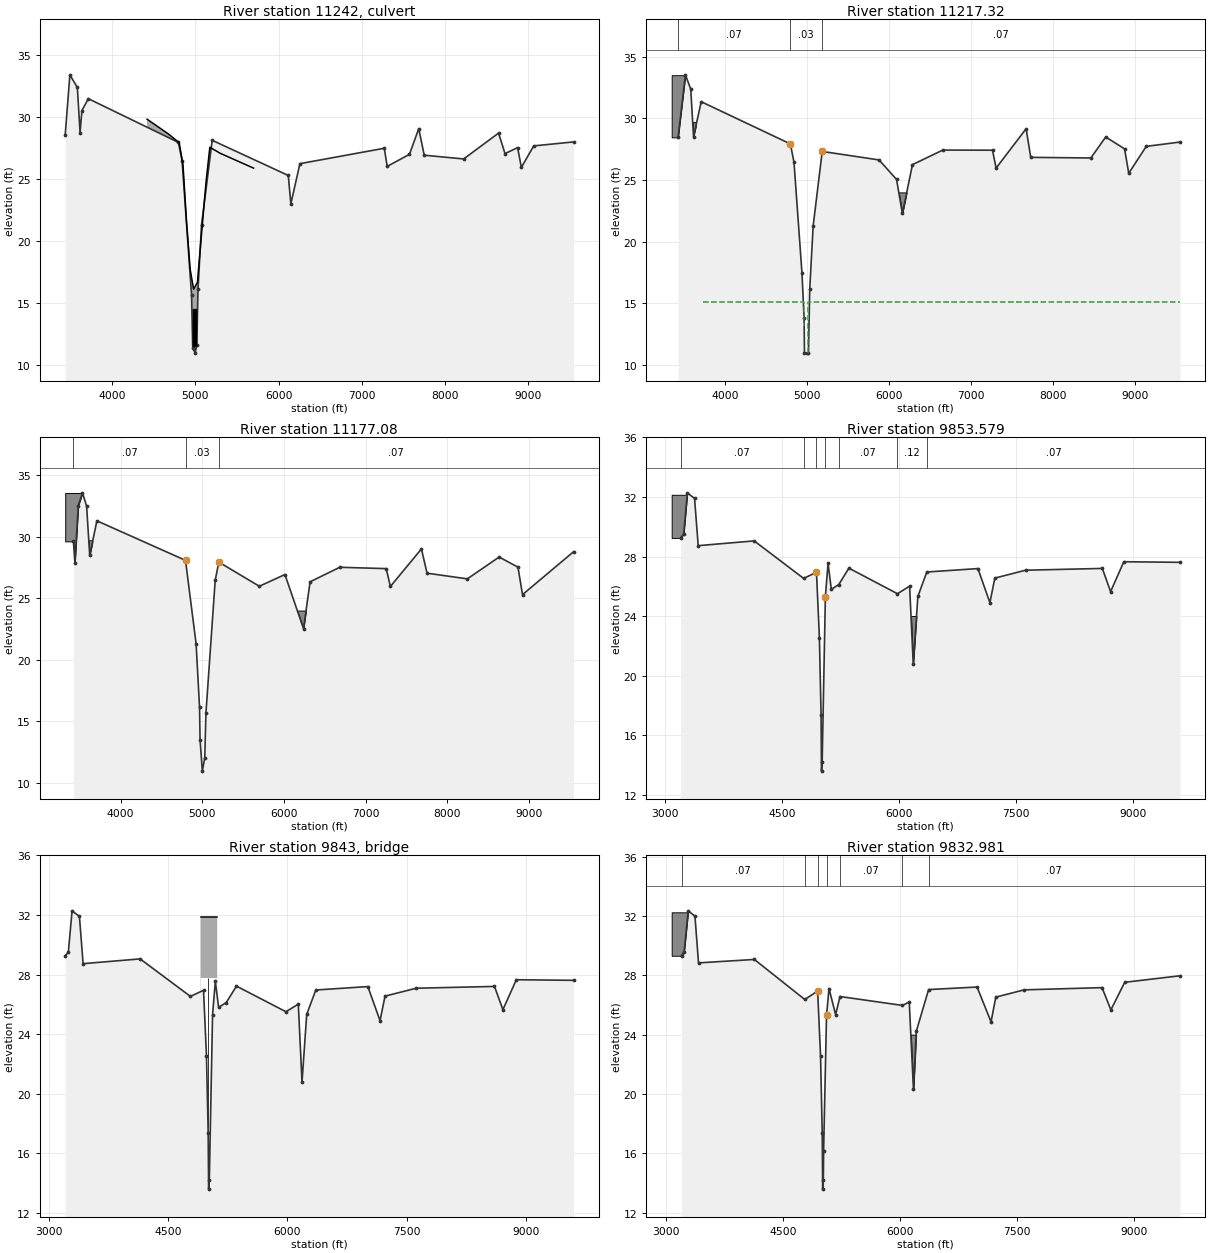
Type RM Length L Ch R = 2 ,11242   ,,,
BEGIN DESCRIPTION:
Culverts at access road
END DESCRIPTION:
Bridge Culvert--1,0,-1,-1, 0
Deck Dist Width WeirC Skew NumUp NumDn MinLoCord MaxHiCord MaxSubmerge Is_Ogee
5,31,2.6,0, 14, 14, , , 0.95, 0, 0,0,,
    4420    4674    4806    4852    4894    4938    4979    5026    5037    5081
    5128    5174    5300    5700
    29.8   28.62   27.91   26.11   21.58   17.72   16.12   16.67   17.66   21.07
    24.7   27.54   27.05   25.86
       0       0       0       0       0       0       0       0       0       0
       0       0       0       0
    4420    4674    4806    4852    4894    4938    4979    5026    5037    5081
    5128    5174    5300    5700
    29.8   28.62   27.91   26.11   21.58   17.72   16.12   16.67   17.66   21.07
    24.7   27.54   27.05   25.86
       0       0       0       0       0       0       0       0       0       0
       0       0       0       0
Multiple Barrel Culv=2,3,6,31,0.012,0.5,1,10,1,11.51,11.04, 6,Culvert #1  , 0 ,5
  4972.5  4972.5  4979.5  4979.5  4986.5  4986.5  4993.5  4993.5  5000.5  5000.5
  5007.5  5007.5
Culvert Bottom n=0.012
BC Design=,, 0 ,, 0 ,,,,,,
BC HTab HWMax=33.37
BC Use User HTab Curves=0
BC User HTab FreeFlow(D)= 0

Type RM Length L Ch R = 1 ,11217.32,41.08,40.25,50.1
BEGIN DESCRIPTION:
access road
END DESCRIPTION:
XS GIS Cut Line= 5
      3181944.56     13779870.35     3181175.417     13778632.21
     3181028.359    13778460.335     3180962.497    13778396.355
     3177937.694    13775285.038
#Sta/Elev= 30
 3428.46   28.46  3518.1   33.53    3583   32.37 3616.92   28.52 3710.54   31.35
 4796.46   27.93 4840.61   26.46 4937.86   17.48 4963.88   13.81 4968.63   10.98
 4998.17   10.97 5017.01   10.97  5032.5   16.16 5074.39   21.29 5184.62   27.32
  5876.9   26.63 6090.28   25.05 6161.38   22.29 6283.94   26.25 6653.24   27.43
  7259.3   27.42 7303.22   25.97 7668.72   29.16 7725.02   26.84 8457.34   26.79
 8638.36   28.49 8868.08   27.53 8918.98   25.55 9132.18   27.73  9543.4   28.08
#Mann= 3 ,-1 , 0
 3428.46     .07       0 4796.46     .03       0 5184.62     .07       0
#XS Ineff= 3 ,-1
    3729    4965    15.1 3523.58 3728.46    30.6    5015  9543.4    15.1
Permanent Ineff=
       F       F       F
#Block Obstruct= 3 ,-1
 3350.62  3516.8    33.5 3586.04 3644.39    29.7 6058.06 6368.36      24
Bank Sta=4796.46,5184.62
XS Rating Curve= 0 ,0
Exp/Cntr=0.5,0.3

Type RM Length L Ch R = 1 ,11177.08,1710.95,1323.5,800.41
BEGIN DESCRIPTION:
access road
END DESCRIPTION:
XS GIS Cut Line= 5
      3181978.54    13779849.243     3181207.789    13778608.517
     3181057.553    13778432.928     3180990.772    13778368.057
     3177962.527    13775260.182
#Sta/Elev= 30
 3423.05   29.61 3441.22   27.89 3482.82   32.52 3534.26   33.55 3584.66   32.47
 3622.74   28.47 3710.36   31.28  4795.6   28.07 4925.61   21.29  4967.5   16.16
 4973.94    13.5 5001.83   10.97 5031.37   12.07 5045.68   15.67 5159.39   26.46
 5203.54   27.93 5699.66   25.97 6013.02   26.92 6240.68   22.53 6321.14   26.33
 6684.56   27.51 7253.62    27.4 7304.26   25.95 7684.82      29 7753.38   27.03
 8246.86   26.57 8636.02   28.34 8866.92   27.52 8922.34   25.29 9547.14   28.77
#Mann= 3 ,-1 , 0
 3423.05     .07       0  4795.6     .03       0 5203.54     .07       0
#XS Ineff= 1 ,-1
    3525    3725    30.5
Permanent Ineff=
       F
#Block Obstruct= 3 ,-1
 3322.52 3534.57   33.54 3591.05 3654.43    29.7 6099.25 6323.21      24
Bank Sta=4795.6,5203.54
XS Rating Curve= 0 ,0
Exp/Cntr=0.3,0.1

Type RM Length L Ch R = 1 ,9853.579,20.09,20.6,21.08
BEGIN DESCRIPTION:
Pipe
END DESCRIPTION:
XS GIS Cut Line= 6
      3183471.69    13778048.058      3181849.41    13777419.695
     3181743.585    13777377.789     3181547.757    13777280.122
     3180155.501    13776757.205     3178103.947    13774794.824
#Sta/Elev= 30
    3202   29.25 3241.52   29.51 3288.48   32.28 3380.99    31.9 3427.36   28.73
 4145.11   29.05 4778.32   26.53 4943.09   26.94 4980.26   22.54 5001.58   17.37
 5007.28   13.58 5015.98   14.21 5056.91    25.3  5091.3   27.54  5133.3   25.79
 5229.19   26.12  5358.1   27.22 5980.64    25.5 6136.15   26.01 6182.74   20.77
 6241.97   25.32 6356.37   26.96 7011.36   27.19 7164.92    24.9 7227.94   26.55
 7621.64   27.08 8605.39    27.2 8711.48   25.64 8880.53   27.65 9600.58   27.61
#Mann= 7 ,-1 , 0
    3202     .07       0 4778.32     .12       0 4943.09     .03       0
 5056.91     .12       0 5229.19     .07       0 5980.64     .12       0
 6356.37     .07       0
#XS Ineff= 2 , 0
         4904.56   25.77 5103.47           25.31
Permanent Ineff=
       F       F
#Block Obstruct= 3 ,-1
  3087.6 3302.62   32.15                         6120.77 6249.95      24
Bank Sta=4943.09,5056.91
XS Rating Curve= 0 ,0
Exp/Cntr=0.3,0.1

Type RM Length L Ch R = 3 ,9843    ,,,
BEGIN DESCRIPTION:
Pipe crossing
END DESCRIPTION:
Bridge Culvert--1,0,-1,-1, 0
Deck Dist Width WeirC Skew NumUp NumDn MinLoCord MaxHiCord MaxSubmerge Is_Ogee
5,10,2.6,0, 6, 6, , , 0.95, 0, 0,0,,
    4905    4909    4909    5111    5111    5115
   31.85   31.85   31.85   31.85   31.85   31.85
       0       0   27.77   27.77       0       0
    4905    4909    4909    5111    5111    5115
   31.85   31.85   31.85   31.85   31.85   31.85
       0       0   27.77   27.77       0       0
Pier Skew, UpSta & Num, DnSta & Num=  ,5000, 4 ,5000, 4 , 3 , 3 , 0 ,,
    1.15    1.15       2       2
       0   25.77   25.77      28
    1.15    1.15       2       2
       0   25.77   25.77      28
BR Coef=-1 , 1 , 0 ,, 0 ,,,0.8,-1,2,0,
WSPro=,,,, 1 ,,,, 0 ,,,, 0 ,,,,-1 ,-1 ,-1 , 0 , 0 , 0 , 0 , 0
BC Design=,, 0 ,, 0 ,,,,,,
BC HTab HWMax=32.28
BC Use User HTab Curves=0
BC User HTab FreeFlow(D)= 0

Type RM Length L Ch R = 1 ,9832.981,1692.79,1291.58,208.05
BEGIN DESCRIPTION:
Pipe
END DESCRIPTION:
XS GIS Cut Line= 6
      3183478.92    13778029.411     3181856.635    13777401.045
     3181751.745    13777359.509     3181555.758    13777261.763
     3180166.367    13776739.922     3178118.151    13774780.813
#Sta/Elev= 30
 3198.01   29.32  3230.4   29.55 3283.94   32.35 3370.12   31.99 3415.88   28.84
 4131.76   29.07    4778   26.37 4943.09   26.94 4980.26   22.54 5001.58   17.37
 5007.28   13.58 5015.98   14.21 5019.37   16.15 5056.91    25.3  5088.4   27.11
  5173.2   25.35 5229.54   26.57 6030.46   25.97 6117.24    26.2 6171.22    20.3
 6208.16   24.24 6365.52   27.04 6986.74   27.21 7165.68   24.86 7226.76   26.53
 7590.12   27.02  8588.7   27.17 8702.08   25.67 8879.34   27.53 9588.03   27.97
#Mann= 7 ,-1 , 0
 3198.01     .07       0    4778     .12       0 4943.09     .03       0
 5056.91     .12       0 5229.54     .07       0 6030.46     .12       0
 6365.52     .07       0
#XS Ineff= 2 , 0
         4912.59   25.74  5097.4           25.32
Permanent Ineff=
       F       F
#Block Obstruct= 3 ,-1
 3071.67 3294.65   32.25                         6087.27 6257.57      24
Bank Sta=4943.09,5056.91
XS Rating Curve= 0 ,0
Exp/Cntr=0.3,0.1

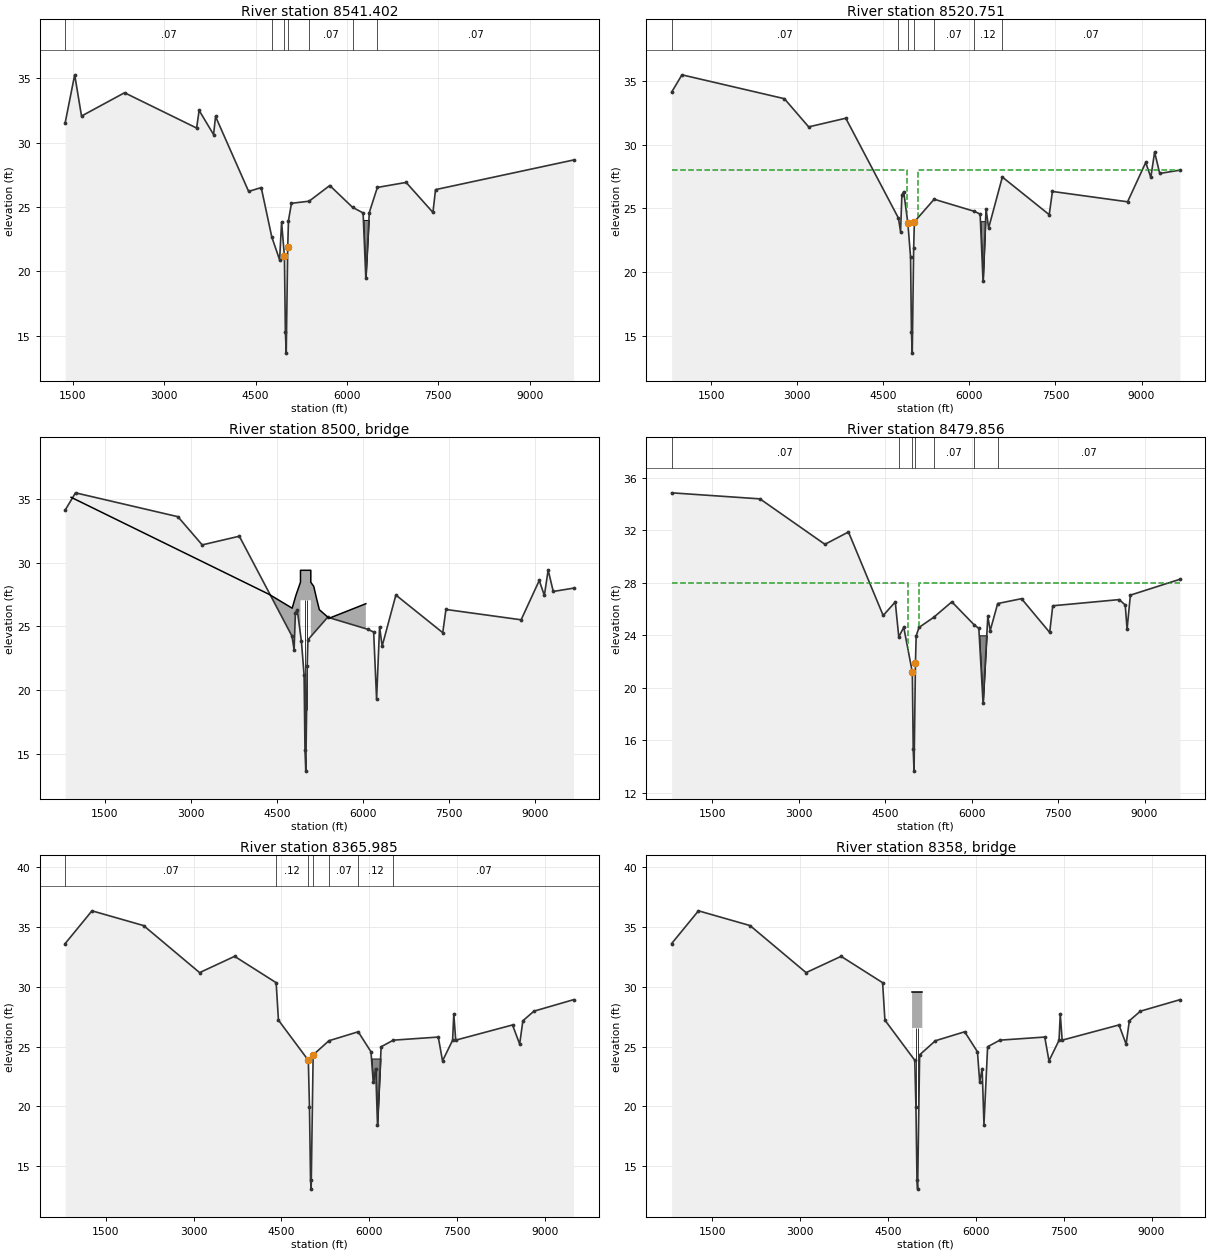
Type RM Length L Ch R = 1 ,8541.402,21.05,20.65,40.76
BEGIN DESCRIPTION:
access road
END DESCRIPTION:
XS GIS Cut Line= 6
      3185305.62    13775821.809     3183495.582    13775258.174
      3182272.49    13776150.358     3181785.978    13776520.468
     3180328.925    13776624.809     3178210.956    13774693.324
#Sta/Elev= 30
 1372.66   31.55 1528.41   35.26 1640.56   32.06 2347.11   33.87 3530.74   31.13
 3572.03    32.5 3809.46   30.62  3841.6   32.03  4385.2   26.21 4591.91   26.51
 4765.45   22.67  4893.7    20.9 4926.39   23.82 4972.96   21.19  4988.4   15.31
 5002.65   13.66 5027.04   21.86 5039.34   23.95 5088.56   25.29 5377.32   25.45
 5717.56   26.67 6091.16   24.98 6265.05   24.54 6309.84   19.46 6366.65   24.57
 6499.07   26.52 6971.55   26.91 7411.92   24.58 7454.71   26.35 9720.97   28.65
#Mann= 7 ,-1 , 0
 1372.66     .07       0 4765.45     .12       0 4972.96     .03       0
 5027.04     .12       0 5377.32     .07       0 6091.16     .12       0
 6499.07     .07       0
#Block Obstruct= 1 ,-1
 6264.84 6408.49      24
Bank Sta=4972.96,5027.04
XS Rating Curve= 0 ,0
Exp/Cntr=0.5,0.3

Type RM Length L Ch R = 1 ,8520.751,45.81,40.9,33.73
BEGIN DESCRIPTION:
access road
END DESCRIPTION:
XS GIS Cut Line= 6
      3185481.51    13773783.958     3182260.512     13776134.34
     3182074.249    13776272.396     3181812.063     13776475.75
     3180353.338    13776582.446     3178246.335    13774663.373
#Sta/Elev= 30
  807.47   34.12  987.02   35.47 2772.48    33.6 3196.28   31.39 3843.46   32.07
 4761.74   24.24 4798.82   23.17  4821.5   26.06 4853.33   26.31 4926.39   23.82
 4972.96   21.19  4988.4   15.31 5002.65   13.66 5027.04   21.86 5039.34   23.95
 5384.18   25.72 6079.78   24.78    6186   24.56 6237.04   19.29  6289.1   24.97
 6334.14   23.46 6573.32   27.46 7390.78   24.51 7446.44   26.33 8757.34   25.52
 9073.34    28.6 9162.56   27.43 9228.52   29.42 9317.62   27.74 9671.17      28
#Mann= 7 ,-1 , 0
  807.47     .07       0 4761.74     .12       0 4926.39     .03       0
 5039.34     .12       0 5384.18     .07       0 6079.78     .12       0
 6573.32     .07       0
#XS Ineff= 2 , 0
       0    4905      28    5095       0      28
Permanent Ineff=
       F       F
#Block Obstruct= 1 ,-1
 6185.62 6282.46      24
Bank Sta=4926.39,5039.34
XS Rating Curve= 0 ,0
Exp/Cntr=0.5,0.3

Type RM Length L Ch R = 3 ,8500    ,,,
BEGIN DESCRIPTION:
Bridge at access road
END DESCRIPTION:
Bridge Culvert--1,0,-1,-1, 0
Deck Dist Width WeirC Skew NumUp NumDn MinLoCord MaxHiCord MaxSubmerge Is_Ogee
5,20,2.6,0, 15, 15, , , 0.95, 0, 0,0,,
     910    4365    4765    4830    4910    4910    4949    5000    5090    5090
    5141    5192    5239    5409    6050
   35.12   27.51   26.43   27.43   28.47    29.4    29.4    29.4    29.4   28.46
   28.14   27.16   26.31   25.64   26.78
       0       0       0       0       0   27.05   27.05   27.05   27.05       0
       0       0       0       0       0
     910    4365    4765    4830    4910    4910    4949    5000    5090    5090
    5141    5192    5239    5409    6050
   35.12   27.51   26.43   27.43   28.47    29.4    29.4    29.4    29.4   28.46
   28.14   27.16   26.31   25.64   26.78
       0       0       0       0       0   27.05   27.05   27.05   27.05       0
       0       0       0       0       0
Pier Skew, UpSta & Num, DnSta & Num=  ,4983, 4 ,4983, 4 , 3 , 3 , 0 ,,
    1.35    1.35    2.35    2.35
       0    24.7    24.7      28
    1.35    1.35    2.35    2.35
       0    24.7    24.7      28
Pier Skew, UpSta & Num, DnSta & Num=  ,5017, 4 ,5017, 4 , 3 , 3 , 0 ,,
    1.35    1.35    2.35    2.35
       0    24.7    24.7      28
    1.35    1.35    2.35    2.35
       0    24.7    24.7      28
BR Coef=-1 , 1 , 0 ,, 0 ,,,0.8,0,2,0,
WSPro=,,,, 1 ,,,, 0 ,,,, 0 ,,,,-1 ,-1 ,-1 , 0 , 0 , 0 , 0 , 0
BC Design=,, 0 ,, 0 ,,,,,,
BC HTab HWMax=35.47
BC Use User HTab Curves=0
BC User HTab FreeFlow(D)= 0

Type RM Length L Ch R = 1 ,8479.856,223.22,113.87,115.41
BEGIN DESCRIPTION:
access road
END DESCRIPTION:
XS GIS Cut Line= 6
      3185443.18    13773709.313     3182095.966    13776209.823
     3182050.794    13776239.959     3181800.884    13776427.306
     3180374.325    13776547.457     3178274.555    13774634.972
#Sta/Elev= 30
  798.92   34.85 2330.47   34.39 3457.24   30.93 3865.03   31.87 4467.25   25.51
 4677.21   26.54 4737.57   23.88 4824.17   24.61 4972.96   21.19  4988.4   15.31
 5002.65   13.66 5027.04   21.86 5039.34   23.95 5088.56    24.6 5343.18   25.37
 5658.15   26.55 6049.71   24.78  6126.5   24.53 6199.71   18.83 6282.23   25.45
 6323.54   24.36 6453.44   26.42 6866.78   26.79 7355.41   24.22 7408.31   26.25
 8561.06   26.72  8665.4   26.31 8697.47   24.47 8754.96   27.06 9615.46   28.27
#Mann= 7 ,-1 , 0
  798.92     .07       0 4737.57     .12       0 4972.96     .03       0
 5027.04     .12       0 5343.18     .07       0 6049.71     .12       0
 6453.44     .07       0
#XS Ineff= 2 , 0
       0    4905      28    5095       0      28
Permanent Ineff=
       F       F
#Block Obstruct= 1 ,-1
 6126.29 6288.97      24
Bank Sta=4972.96,5027.04
XS Rating Curve= 0 ,0
Exp/Cntr=0.5,0.3

Type RM Length L Ch R = 1 ,8365.985,16.87,15.11,13.12
BEGIN DESCRIPTION:
Pipe
END DESCRIPTION:
XS GIS Cut Line= 6
      3185321.51    13773582.005      3182368.95    13775744.972
     3182036.313    13776106.021     3181831.127     13776312.12
     3180321.163    13776436.293     3178306.549    13774607.959
#Sta/Elev= 30
  808.79    33.6 1265.93   36.33 2146.41    35.1 3103.19   31.17 3700.86   32.53
  4409.7   30.33 4449.07    27.2 4958.67   23.85 4978.62   19.92 4996.71   13.82
 5007.32   13.09 5041.33    24.3 5310.15   25.48  5810.4   26.23 6028.52   24.56
  6067.1   22.02 6108.82   23.16  6139.7   18.48 6202.02   24.98  6410.7   25.53
  7177.4   25.79  7249.8    23.8 7421.74   25.52 7442.25   27.72 7474.83   25.53
 8444.79    26.8 8566.46    25.2 8621.69   27.15 8810.02   27.95 9486.25   28.91
#Mann= 7 ,-1 , 0
  808.79     .07       0  4409.7     .12       0 4958.67     .03       0
 5041.33     .12       0 5310.15     .07       0  5810.4     .12       0
  6410.7     .07       0
#XS Ineff= 2 , 0
       0 4958.67   23.85 5041.33       0    24.3
Permanent Ineff=
       F       F
#Block Obstruct= 2 ,-1
 6025.08 6240.73      24 9279.07 9430.98   28.51
Bank Sta=4958.67,5041.33
XS Rating Curve= 0 ,0
Exp/Cntr=0.3,0.1

Type RM Length L Ch R = 3 ,8358    ,,,
BEGIN DESCRIPTION:
Pipe crossing
END DESCRIPTION:
Bridge Culvert--1,0,-1,-1, 0
Deck Dist Width WeirC Skew NumUp NumDn MinLoCord MaxHiCord MaxSubmerge Is_Ogee
3,10,2.6,0, 6, 6, , , 0.95, 0, 0,0,,
  4912.5  4915.5  4915.5  5084.5  5084.5  5087.5
   29.55   29.55   29.55   29.55   29.55   29.55
       0       0   26.55   26.55       0       0
  4912.5  4915.5  4915.5  5084.5  5084.5  5087.5
   29.55   29.55   29.55   29.55   29.55   29.55
       0       0   26.55   26.55       0       0
Pier Skew, UpSta & Num, DnSta & Num=  ,4979, 4 ,4979, 4 , 3 , 3 , 0 ,,
    1.15    1.15       2       2
       0   24.55   24.55      27
    1.15    1.15       2       2
       0   24.55   24.55      27
Pier Skew, UpSta & Num, DnSta & Num=  ,5021, 4 ,5021, 4 , 3 , 3 , 0 ,,
    1.15    1.15       2       2
       0   24.55   24.55      27
    1.15    1.15       2       2
       0   24.55   24.55      27
BR Coef=-1 , 1 , 0 ,, 0 ,,,0.8,-1,2,0,
WSPro=,,,, 1 ,,,, 0 ,,,, 0 ,,,,-1 ,-1 ,-1 , 0 , 0 , 0 , 0 , 0
BC Design=,, 0 ,, 0 ,,,,,,
BC HTab HWMax=36.33
BC Use User HTab Curves=0
BC User HTab FreeFlow(D)= 0

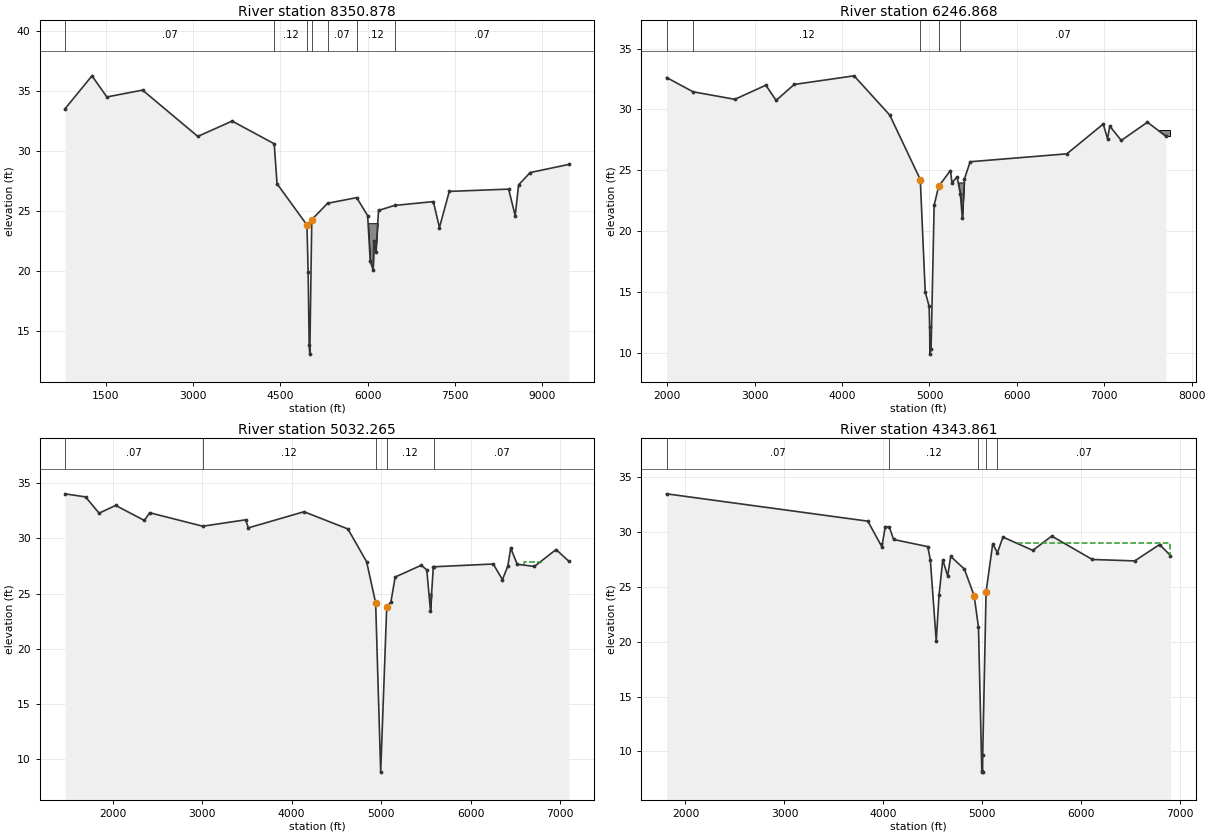
Type RM Length L Ch R = 1 ,8350.878,1425.46,2104.01,879.43
BEGIN DESCRIPTION:
Pipe
END DESCRIPTION:
XS GIS Cut Line= 6
      3185312.64    13773569.904     3182358.896    13775733.743
     3182025.374    13776095.757     3181821.248    13776300.795
     3180338.461    13776421.718     3178320.664    13774597.222
#Sta/Elev= 30
  804.18   33.53  1267.3   36.28 1523.12   34.52 2135.96   35.09 3084.62   31.23
  3673.4   32.51  4396.1   30.62 4444.68   27.29 4958.67   23.85 4978.62   19.92
 4996.71   13.82 5007.32   13.09 5041.33    24.3 5312.48   25.66 5811.38   26.13
  6000.7   24.63  6045.1   20.81  6094.1   20.13 6106.62   22.48 6141.98   21.64
 6187.38   25.06 6461.72   25.48 7128.54    25.8 7233.08   23.64 7401.96   26.65
 8421.08   26.84 8533.28   24.63 8592.38    27.2 8791.64   28.22 9455.35    28.9
#Mann= 7 ,-1 , 0
  804.18     .07       0  4396.1     .12       0 4958.67     .03       0
 5041.33     .12       0 5312.48     .07       0 5811.38     .12       0
 6461.72     .07       0
#XS Ineff= 2 , 0
       0 4958.67   23.85 5041.33       0    24.3
Permanent Ineff=
       F       F
#Block Obstruct= 2 ,-1
 5999.64 6314.64      24  9255.1 9426.15   28.51
Bank Sta=4958.67,5041.33
XS Rating Curve= 0 ,0
Exp/Cntr=0.3,0.1

Type RM Length L Ch R = 1 ,6246.868,354.19,1214.6,1200.65
XS GIS Cut Line= 6
      3183428.14    13774291.246     3180894.665    13774983.012
     3180715.744    13775193.917     3180575.374    13775350.684
     3180020.622    13775641.509     3178383.053    13774539.822
#Sta/Elev= 30
 1991.98   32.62 2294.45   31.45 2772.71   30.83 3127.65   31.99 3245.19   30.74
 3451.71   32.05 4137.11   32.76 4545.02   29.54 4894.79   24.24 4951.49      15
 4996.11   13.82 5001.94    12.1    5005    9.89 5018.22   10.29 5053.51   22.13
 5105.21   23.68 5240.06   24.98 5257.49   23.97 5315.85   24.46 5353.06   23.06
 5375.84   21.07 5400.53    24.3 5465.35    25.7 6572.26   26.35 6988.21    28.8
 7037.58   27.59 7062.86   28.63 7194.69   27.45 7494.23   28.95 7705.23   27.79
#Mann= 5 ,-1 , 0
 1991.98     .07       0 2294.45     .12       0 4894.79     .04       0
 5105.21     .12       0 5353.06     .07       0
#XS Ineff= 1 ,-1
    6980    7400    28.2
Permanent Ineff=
       F
#Block Obstruct= 2 ,-1
 5318.47 5419.72      24    7500 7757.72   28.31
Bank Sta=4894.79,5105.21
XS Rating Curve= 0 ,0
Exp/Cntr=0.3,0.1

Type RM Length L Ch R = 1 ,5032.265,890.28,688.4,395.74
XS GIS Cut Line= 6
      3183925.84    13773796.606     3180993.068    13774589.348
     3180578.664    13774466.239     3179897.445    13774399.054
     3179158.829    13774603.574      3178462.59    13774477.959
#Sta/Elev= 30
 1467.65   34.03 1697.92   33.75  1848.7   32.28 2033.86   32.98 2354.43   31.62
 2413.86   32.32 3006.62    31.1 3485.98   31.68  3515.6   30.95 4138.05   32.41
 4628.31   30.85 4837.49   27.88 4938.19   24.16 4994.49    8.85 5061.81   23.78
 5108.24   24.23 5156.22    26.5 5448.38   27.57 5509.29   27.15 5550.85   23.45
 5582.21   27.41 5588.33   27.43 6251.38   27.68 6354.86   26.27 6414.37   27.49
 6447.13   29.13 6518.97   27.66 6711.22   27.46 6954.25   28.99  7096.9   27.92
#Mann= 5 ,-1 , 0
 1467.65     .07       0 3006.62     .12       0 4938.19     .04       0
 5061.81     .12       0 5588.33     .07       0
#XS Ineff= 1 ,-1
    6600    6800    27.9
Permanent Ineff=
       F
#Block Obstruct= 1 ,-1
 5498.53 5596.76      25
Bank Sta=4938.19,5061.81
XS Rating Curve= 0 ,0
Exp/Cntr=0.3,0.1

Type RM Length L Ch R = 1 ,4343.861,270.64,435.52,561.82
XS GIS Cut Line= 6
      3183508.46     13773442.47     3180947.209    13773666.933
     3180392.313    13773834.782     3180320.168     13773860.91
     3178878.505    13774285.409      3178533.29    13774398.421
#Sta/Elev= 30
 1808.83   33.47 3843.16   30.98 3984.64   28.65  4019.8   30.49 4060.38   30.44
 4103.72   29.31 4448.96   28.66 4475.12   27.44 4534.58   20.05 4563.08   24.26
 4600.48   27.46 4650.08   25.99 4680.86   27.77 4818.66   26.62 4917.76   24.19
 4961.63   21.31 4995.09    8.23 5000.73    8.12 5003.31    8.16 5004.41    9.67
 5038.37   24.54 5105.47   28.91 5153.49    28.1  5208.8   29.53 5511.16   28.32
 5702.48   29.62 6112.32   27.49 6540.96   27.36 6791.96   28.85 6902.48   27.85
#Mann= 5 ,-1 , 0
 1808.83     .07       0 4060.38     .12       0 4961.63     .04       0
 5038.37     .12       0 5153.49     .07       0
#XS Ineff= 2 ,-1
 4442.81 4680.44    27.7    5350    7000      29
Permanent Ineff=
       F       F
#Block Obstruct= 1 ,-1
    3880    4050      29
Bank Sta=4917.76,5038.37
XS Rating Curve= 0 ,0
Exp/Cntr=0.3,0.1