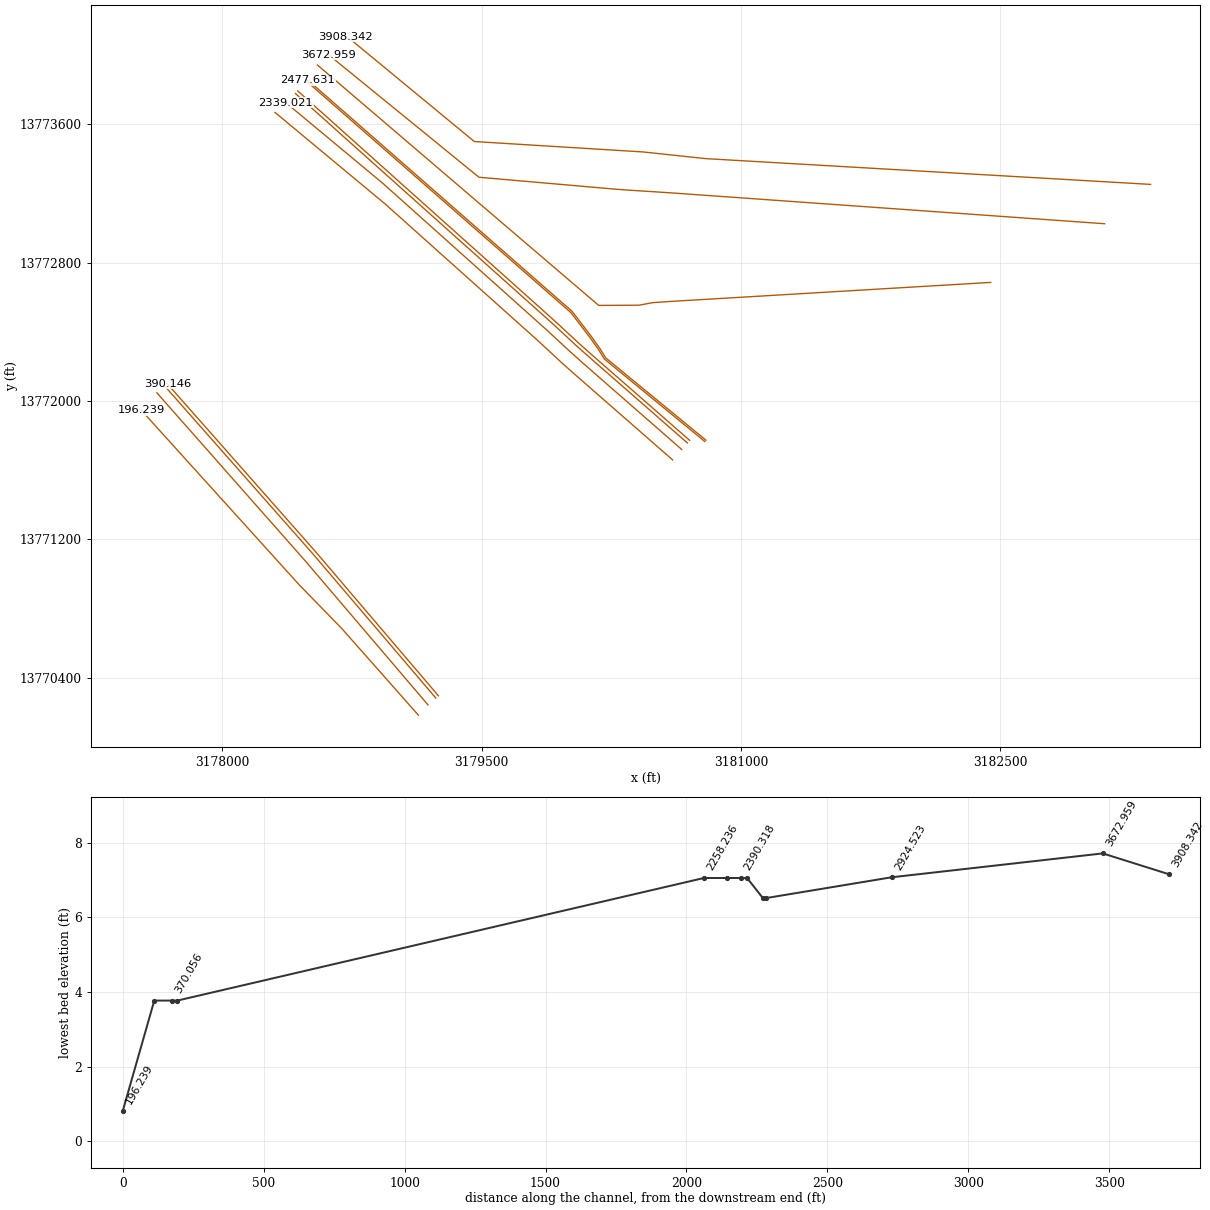
HEC-RAS study A119-00-00.prj: A119-00-00

--- A119-00-00.g01 (geometry) --- (continued)

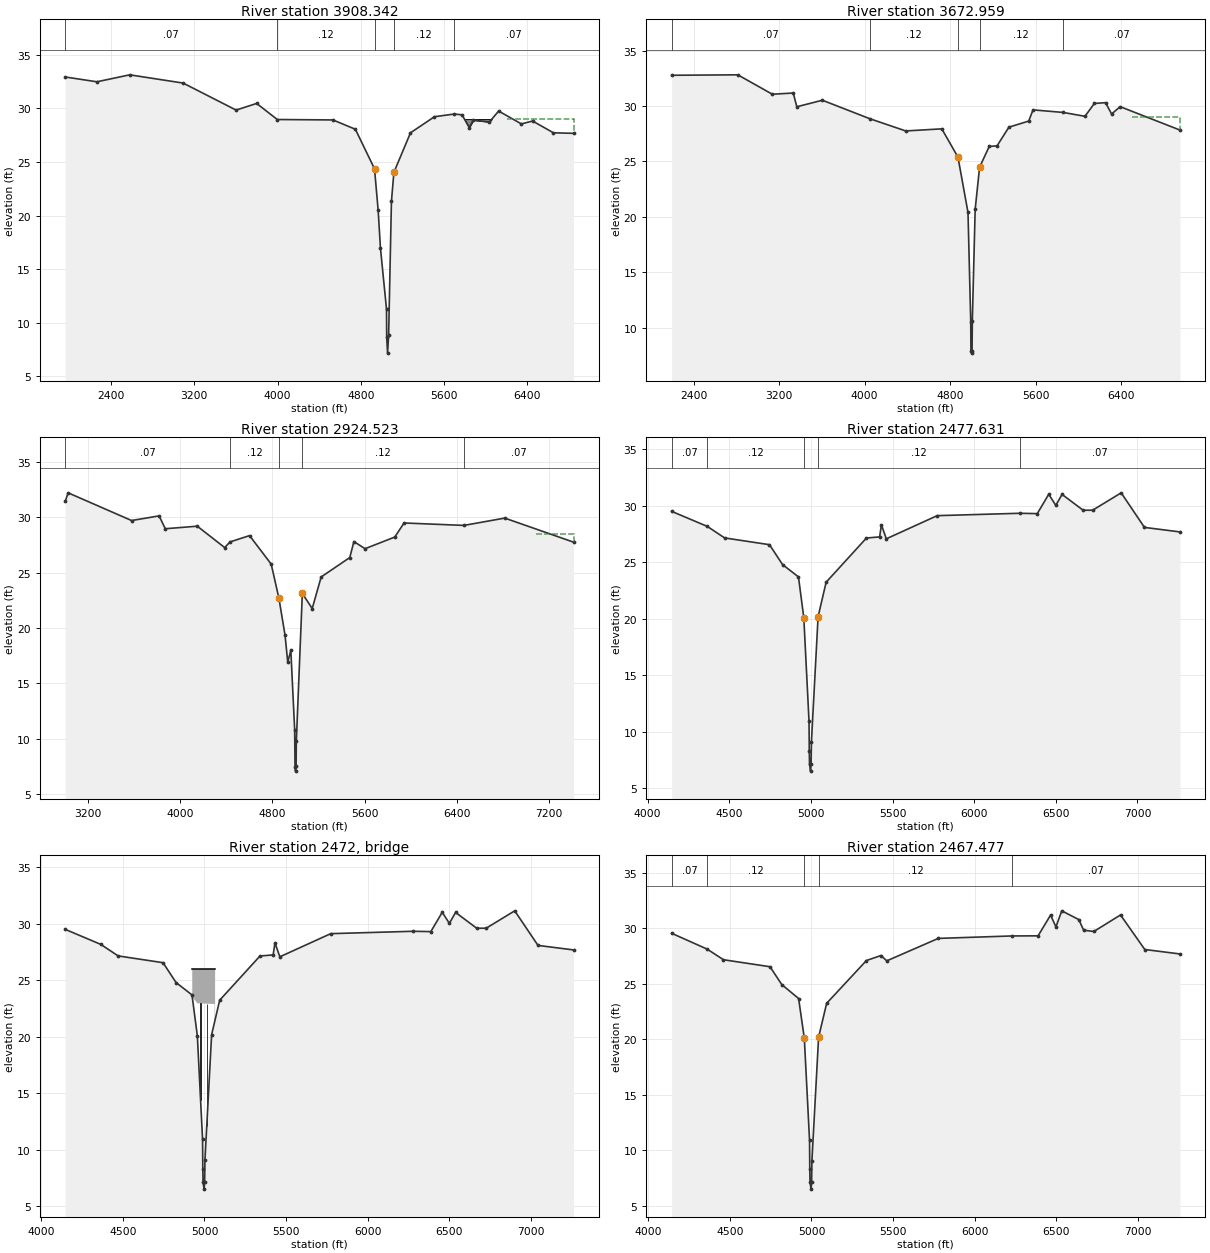
Type RM Length L Ch R = 1 ,3908.342,214.84,235.38,206.79
XS GIS Cut Line= 6
      3183369.34    13773252.754     3180795.841    13773401.833
     3180431.504    13773440.616      3179457.23    13773500.657
     3178753.032    13774081.621     3178713.104    13774108.212
#Sta/Elev= 30
 1961.41   32.93 2265.58   32.48 2580.98   33.13 3093.78   32.36 3602.58   29.84
 3799.91   30.46 3998.03   28.96  4532.7   28.92 4747.79   28.05 4931.71   24.36
  4966.6   20.48 4988.79   16.94 5046.91   11.25 5048.55    8.62 5056.92    7.16
 5067.19    8.84 5094.07   21.32 5117.74   24.03 5277.11   27.72 5507.04   29.22
 5696.28   29.47  5772.2    29.4 5841.19    28.2 5880.53   28.91 6035.13   28.73
 6123.47   29.75 6341.79   28.55 6449.67   28.82 6649.77   27.72 6842.69   27.67
#Mann= 5 ,-1 , 0
 1961.41     .07       0 3998.03     .12       0 4931.71     .04       0
 5117.74     .12       0 5696.28     .07       0
#XS Ineff= 1 ,-1
    6200    6900      29
Permanent Ineff=
       F
#Block Obstruct= 1 ,-1
    5750    6120      29
Bank Sta=4931.71,5117.74
XS Rating Curve= 0 ,0
Exp/Cntr=0.3,0.1

Type RM Length L Ch R = 1 ,3672.959,583.33,748.44,207.5
XS GIS Cut Line= 6
     3183103.739    13773025.095      3180589.21    13773204.186
     3180340.023    13773220.087     3180273.227    13773225.107
     3179484.182    13773294.026     3178612.737    13774003.759
#Sta/Elev= 30
 2195.42   32.77 2813.84   32.81 3136.78   31.06 3332.48   31.17 3365.58   29.93
 3604.52   30.52  4049.3   28.85 4384.38   27.75 4721.38   27.94 4872.64   25.39
 4966.51    20.4 4992.07   10.56  4993.9    7.95 4999.39    7.72  5004.3    7.88
  5007.1   10.66 5033.49   20.68 5074.88   24.48 5164.74   26.35 5238.32   26.41
 5348.96   28.09 5534.06   28.64  5574.6   29.65 5855.64   29.42 6060.42   29.07
    6148   30.23 6252.46    30.3 6309.44   29.28 6389.22   29.94 6948.94   27.83
#Mann= 5 ,-1 , 0
 2195.42     .07       0  4049.3     .12       0 4872.64     .04       0
 5074.88     .12       0 5855.64     .07       0
#XS Ineff= 1 ,-1
    6500    7000      29
Permanent Ineff=
       F
Bank Sta=4872.64,5074.88
XS Rating Curve= 0 ,0
Exp/Cntr=0.3,0.1

Type RM Length L Ch R = 1 ,2924.523,740.7,446.89,121.62
XS GIS Cut Line= 6
     3182444.448    13772685.755     3180592.174     13772575.62
     3180489.352    13772568.638     3180409.969    13772553.847
     3180176.635    13772552.694     3178549.672     13773943.43
#Sta/Elev= 30
 3000.88   31.41 3026.22   32.19  3577.1   29.69 3815.78   30.11 3870.02   28.95
 4147.48   29.18 4385.44   27.25 4431.88   27.76 4601.04   28.33 4789.08   25.76
 4856.44   22.67 4909.82   19.32 4932.78   16.91 4959.63   17.98  4992.9   10.82
  4996.2    7.41 5000.48    7.08  5005.5    7.55 5007.37    9.78 5059.51   23.11
 5145.26   21.75    5223    24.6  5471.3   26.35 5507.28   27.79 5604.16   27.15
 5862.12    28.2 5942.74   29.47 6462.22   29.25 6816.94   29.91 7413.94   27.74
#Mann= 5 ,-1 , 0
 3000.88     .07       0 4431.88     .12       0 4856.44     .04       0
 5059.51     .12       0 6462.22     .07       0
#XS Ineff= 1 ,-1
    7090    7500    28.5
Permanent Ineff=
       F
Bank Sta=4856.44,5059.51
XS Rating Curve= 0 ,0
Exp/Cntr=0.3,0.1

Type RM Length L Ch R = 1 ,2477.631,10,10.15,10.34
BEGIN DESCRIPTION:
Pipe
END DESCRIPTION:
XS GIS Cut Line= 6
      3180796.84    13771773.275     3180216.754    13772249.532
     3180186.193    13772299.639     3180135.707    13772371.023
     3180023.236    13772517.885     3178494.373    13773856.122
#Sta/Elev= 30
 4146.92   29.51 4364.86   28.18 4471.06   27.16 4746.08   26.56  4826.1    24.8
  4923.5   23.71 4956.28   20.09 4988.21   10.93  4989.7    8.32 4991.35    7.12
 4997.61    6.52 5000.96    7.18 5002.78    9.08 5043.72   20.19 5093.05   23.24
 5339.84   27.15 5420.64   27.25 5431.56   28.32 5461.48   27.08 5773.26   29.13
 6277.96   29.34 6386.22   29.31 6456.32   31.02 6499.86   30.04 6537.96   31.01
 6667.18   29.61 6725.12   29.61 6900.18   31.15 7042.74   28.09 7260.38   27.69
#Mann= 5 ,-1 , 0
 4146.92     .07       0 4364.86     .12       0 4956.28     .04       0
 5043.72     .12       0 6277.96     .07       0
#XS Ineff= 2 , 0
       0 4956.28   20.09 5043.72       0   20.19
Permanent Ineff=
       F       F
Bank Sta=4956.28,5043.72
XS Rating Curve= 0 ,0
Exp/Cntr=0.3,0.1

Type RM Length L Ch R = 3 ,2472    ,,,
BEGIN DESCRIPTION:
Pipe crossing
END DESCRIPTION:
Bridge Culvert--1,0,-1,-1, 0
Deck Dist Width WeirC Skew NumUp NumDn MinLoCord MaxHiCord MaxSubmerge Is_Ogee
3,5,2.6,0, 5, 5, , , 0.95, 0, 0,0,,
    4925    4925    5062    5062    5065
   25.99   25.99   25.99   25.99   25.99
       0   22.99    22.9       0       0
    4925    4925    5062    5062    5065
   25.99   25.99   25.99   25.99   25.99
       0   22.99    22.9       0       0
Pier Skew, UpSta & Num, DnSta & Num=  ,4976, 4 ,4976, 4 , 3 , 3 , 0 ,,
     1.2     1.2       2       2
       0   20.99   20.99      24
     1.2     1.2       2       2
       0   20.99   20.99      24
Pier Skew, UpSta & Num, DnSta & Num=  ,5014, 4 ,5014, 4 , 3 , 3 , 0 ,,
     1.2     1.2       2       2
       0   20.99   20.99      24
     1.2     1.2       2       2
       0   20.99   20.99      24
BR Coef=-1 , 1 , 0 ,, 0 ,,,0.8,-1,2,0,
WSPro=,,,, 1 ,,,, 0 ,,,, 0 ,,,,-1 ,-1 ,-1 , 0 , 0 , 0 , 0 , 0
BC Design=,, 0 ,, 0 ,,,,,,
BC HTab HWMax=31.15
BC Use User HTab Curves=0
BC User HTab FreeFlow(D)= 0

Type RM Length L Ch R = 1 ,2467.477,42.51,56.27,93.9
BEGIN DESCRIPTION:
Pipe
END DESCRIPTION:
XS GIS Cut Line= 6
     3180790.494    13771765.546     3180209.099    13772242.879
     3180177.832    13772294.142     3180127.652    13772365.094
     3180015.901    13772511.015     3178487.787    13773848.597
#Sta/Elev= 30
  4143.7   29.54 4361.67   28.11    4461   27.16 4746.19   26.53 4817.82   24.93
 4921.24   23.67 4956.28   20.09 4988.21   10.93  4989.7    8.32 4991.35    7.12
 4997.61    6.52 5000.96    7.18 5002.78    9.08 5043.72   20.19 5093.05   23.24
 5336.85   27.09 5426.06   27.54 5461.35   27.06 5777.02   29.08 6229.96    29.3
 6388.26   29.31 6464.87   31.18 6497.64   30.11 6533.19   31.56 6637.96   30.77
 6667.08   29.82 6729.58    29.7  6893.1   31.19  7041.8   28.08 7257.51   27.68
#Mann= 5 ,-1 , 0
  4143.7     .07       0 4361.67     .12       0 4956.28     .04       0
 5043.72     .12       0 6229.96     .07       0
#XS Ineff= 2 , 0
       0 4956.28   20.09 5043.72       0   20.19
Permanent Ineff=
       F       F
Bank Sta=4956.28,5043.72
XS Rating Curve= 0 ,0
Exp/Cntr=0.3,0.1

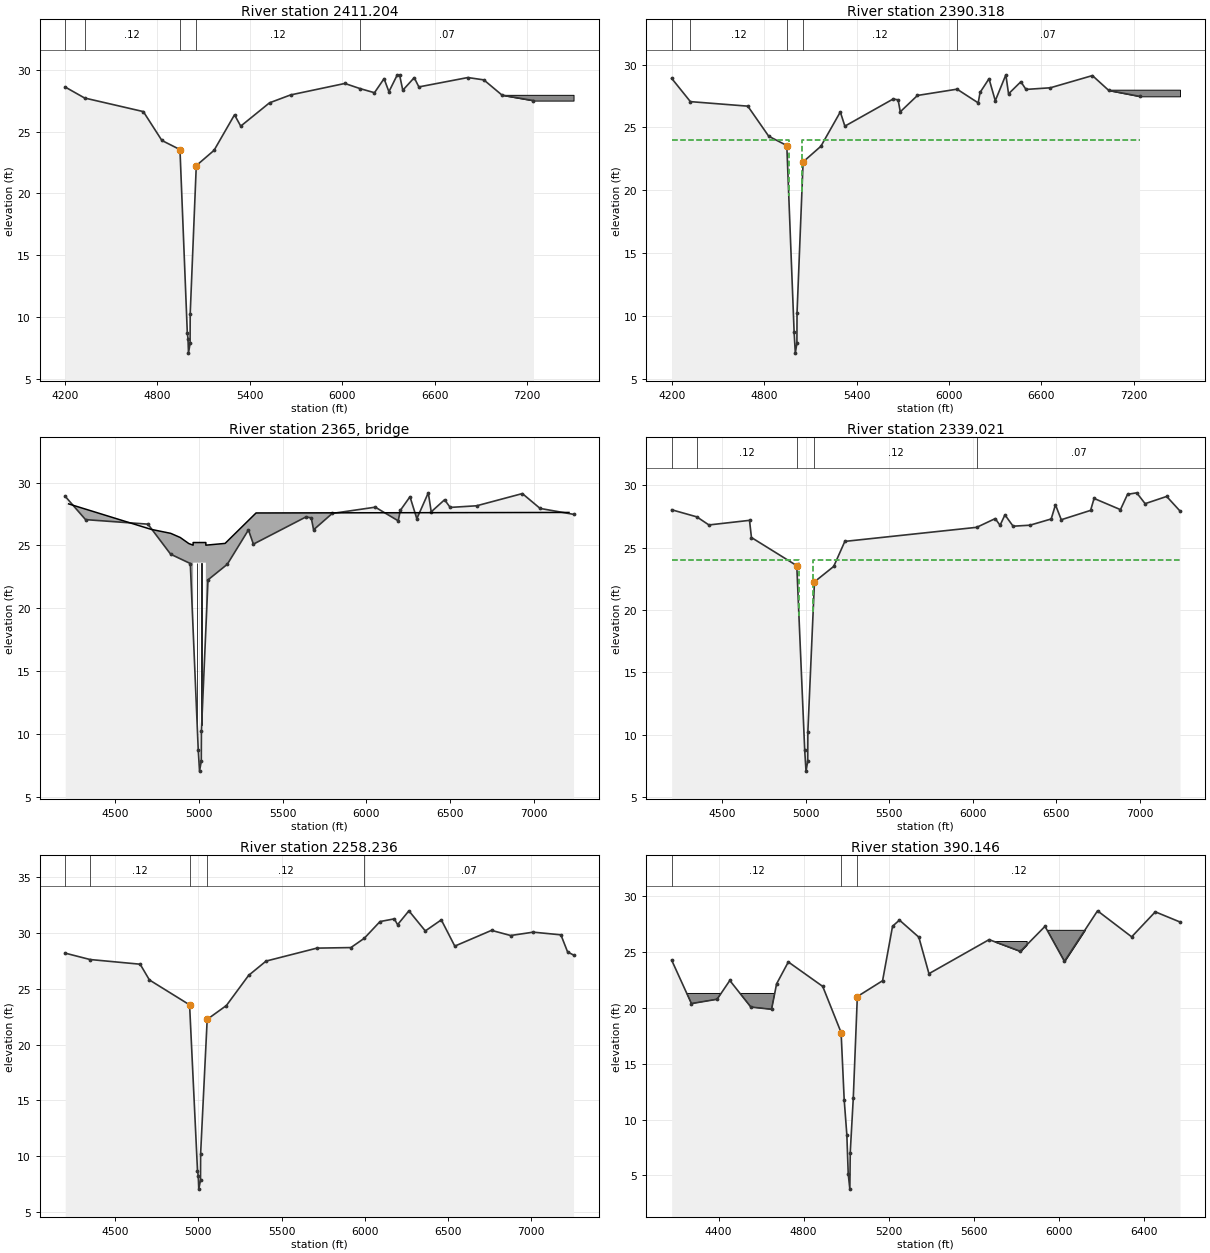
Type RM Length L Ch R = 1 ,2411.204,20.03,20.89,20.15
BEGIN DESCRIPTION:
Beamer Road
END DESCRIPTION:
XS GIS Cut Line= 5
     3180702.949    13771772.078     3180139.899    13772264.369
     3180061.076    13772334.475     3179927.546    13772458.394
     3178435.829    13773793.314
#Sta/Elev= 30
 4202.68   28.63 4328.66   27.74 4709.42   26.64  4829.7    24.3 4947.11   23.56
 4994.65    8.72 4999.15    8.24 5002.35    7.06  5012.7    7.85 5013.47   10.24
 5052.89   22.26 5168.26    23.5  5300.9   26.38 5341.24   25.46 5527.88   27.35
 5664.44   27.99 6016.62   28.92 6116.24    28.5 6208.78   28.17 6270.98   29.31
 6302.46   28.25 6356.84   29.62 6371.62   29.61 6392.56   28.37 6466.62   29.39
 6496.72   28.64 6814.48    29.4 6918.16   29.21 7036.72   27.97 7240.06   27.53
#Mann= 5 ,-1 , 0
 4202.68     .07       0 4328.66     .12       0 4947.11    .045       0
 5052.89     .12       0 6116.24     .07       0
#Block Obstruct= 1 ,-1
    7000    7500      28
Bank Sta=4947.11,5052.89
XS Rating Curve= 0 ,0
Exp/Cntr=0.5,0.3

Type RM Length L Ch R = 1 ,2390.318,50.08,51.3,50.14
BEGIN DESCRIPTION:
Beamer Road
END DESCRIPTION:
XS GIS Cut Line= 5
     3180689.785    13771757.022     3180126.671    13772249.368
     3180047.626    13772319.671     3179914.074    13772443.611
     3178422.492     13773778.41
#Sta/Elev= 30
 4199.59    28.9 4321.09   27.05 4693.96   26.69  4829.7    24.3 4947.11   23.56
 4994.65    8.72 5002.35    7.06  5012.7    7.85 5013.47   10.24 5052.89   22.26
 5168.26    23.5 5294.57   26.23 5324.11    25.1 5637.77   27.26 5669.83   27.19
 5683.86   26.24 5795.22   27.54 6052.53   28.04 6189.83   26.95 6201.92   27.78
 6259.93   28.87 6300.71   27.12 6369.32   29.18 6386.83   27.67  6466.7   28.63
 6500.04   28.02 6658.13   28.15 6931.33   29.12 7037.49   27.94  7237.2   27.47
#Mann= 5 ,-1 , 0
 4199.59     .07       0 4321.09     .12       0 4947.11    .045       0
 5052.89     .12       0 6052.53     .07       0
#XS Ineff= 2 , 0
       0    4960      24    5045       0      24
Permanent Ineff=
       F       F
#Block Obstruct= 1 ,-1
    7000    7500      28
Bank Sta=4947.11,5052.89
XS Rating Curve= 0 ,0
Exp/Cntr=0.5,0.3

Type RM Length L Ch R = 3 ,2365    ,,,
BEGIN DESCRIPTION:
Bridge at Beamer Road
END DESCRIPTION:
Bridge Culvert--1,0,-1,-1, 0
Deck Dist Width WeirC Skew NumUp NumDn MinLoCord MaxHiCord MaxSubmerge Is_Ogee
5,25,2.6,0, 13, 13, , , 0.95, 0, 0,0,,
    4220    4712    4830    4887    4938    4964    4964    5013    5040    5040
    5155    5340    7210
    28.3   26.28   25.96   25.63   25.15   25.02   25.23   25.23   25.23   25.02
   25.16   27.58   27.62
       0       0       0       0       0       0   23.63   23.63   23.63       0
       0       0       0
    4220    4712    4830    4887    4938    4964    4964    5013    5040    5040
    5155    5340    7210
    28.3   26.28   25.96   25.63   25.15   25.02   25.23   25.23   25.23   25.02
   25.16   27.58   27.62
       0       0       0       0       0       0   23.63   23.63   23.63       0
       0       0       0
Pier Skew, UpSta & Num, DnSta & Num=  ,4989, 4 ,4989, 4 , 3 , 3 , 0 ,,
    1.35    1.35       2       2
       0   21.63   21.63      24
    1.35    1.35       2       2
       0   21.63   21.63      24
Pier Skew, UpSta & Num, DnSta & Num=  ,5015, 4 ,5015, 4 , 3 , 3 , 0 ,,
    1.35    1.35       2       2
       0   21.63   21.63      24
    1.35    1.35       2       2
       0   21.63   21.63      24
BR Coef=-1 , 1 , 0 ,, 0 ,,,0.8,0,2,0,
WSPro=,,,, 1 ,,,, 0 ,,,, 0 ,,,,-1 ,-1 ,-1 , 0 , 0 , 0 , 0 , 0
BC Design=,, 0 ,, 0 ,,,,,,
BC HTab HWMax=29.18
BC Use User HTab Curves=0
BC User HTab FreeFlow(D)= 0

Type RM Length L Ch R = 1 ,2339.021,80.13,80.79,80.22
BEGIN DESCRIPTION:
Beamer Road
END DESCRIPTION:
XS GIS Cut Line= 6
     3180656.874     13771719.38       3180093.6    13772211.866
     3180014.002    13772282.662     3179880.394    13772406.653
     3178929.411    13773257.677     3178367.463    13773725.012
#Sta/Elev= 30
 4197.88   28.05 4348.42   27.48 4420.98   26.83    4664    27.2 4675.62   25.82
 4947.11   23.56 4994.65    8.72 5002.35    7.06  5012.7    7.85 5013.47   10.24
 5052.89   22.26 5168.26    23.5  5234.9   25.51 6024.64   26.64 6135.46   27.34
 6164.36    26.8 6193.64   27.64 6242.46   26.73 6343.32   26.81 6470.68   27.31
 6496.22   28.45    6531   27.25 6706.54      28  6727.4   28.96 6885.36   28.06
 6927.76   29.29 6982.76   29.41 7033.18   28.54 7162.18   29.12 7241.96   27.95
#Mann= 5 ,-1 , 0
 4197.88     .07       0 4348.42     .12       0 4947.11    .045       0
 5052.89     .12       0 6024.64     .07       0
#XS Ineff= 2 , 0
       0    4960      24    5045       0      24
Permanent Ineff=
       F       F
Bank Sta=4947.11,5052.89
XS Rating Curve= 0 ,0
Exp/Cntr=0.5,0.3

Type RM Length L Ch R = 1 ,2258.236,1894.66,1868.09,1742.55
BEGIN DESCRIPTION:
Beamer Road
END DESCRIPTION:
XS GIS Cut Line= 6
     3180604.217    13771659.154     3180040.688    13772151.863
     3179960.203    13772223.447     3179826.506    13772347.522
     3178944.172    13773137.111     3178304.389    13773668.946
#Sta/Elev= 30
 4199.68   28.19 4348.92   27.62 4650.02    27.2 4705.76   25.79 4947.11   23.56
 4994.65    8.72 4999.15    8.24 5002.35    7.06  5012.7    7.85 5013.47   10.24
 5052.89   22.26 5168.26    23.5 5301.88    26.2 5406.74   27.48 5712.14   28.64
 5916.46   28.69 5996.86   29.52  6091.5   31.02 6177.22   31.26 6197.02   30.74
 6265.02   31.98 6363.66   30.18 6459.78   31.17  6540.8   28.82 6761.54   30.23
 6876.28   29.77  7012.2   30.07 7178.42   29.83 7218.68    28.3 7254.36   28.02
#Mann= 5 ,-1 , 0
 4199.68     .07       0 4348.92     .12       0 4947.11    .045       0
 5052.89     .12       0 5996.86     .07       0
Bank Sta=4947.11,5052.89
XS Rating Curve= 0 ,0
Exp/Cntr=0.3,0.1

Type RM Length L Ch R = 1 ,390.146 ,20,20.09,20.48
BEGIN DESCRIPTION:
access road
END DESCRIPTION:
XS GIS Cut Line= 4
     3179249.753    13770294.157      3178794.77    13770827.821
     3178538.088    13771128.995     3177680.823    13772099.919
#Sta/Elev= 30
 4179.46   24.28 4272.44   20.39 4393.32   20.78 4453.06   22.46 4552.06   20.08
 4649.58   19.88 4673.22   22.16 4728.42   24.12 4890.31   21.93  4976.8    17.8
 4991.36   11.77 5003.79    8.65 5010.37    5.13    5018    3.77 5019.81    7.05
 5034.13   11.93  5053.2   21.02 5172.02   22.44 5218.92   27.32 5251.36   27.87
  5342.6   26.34 5390.24   23.07 5673.34   26.12 5820.62   25.07 5936.38   27.31
  6027.8   24.17  6183.6    28.7 6344.26   26.37  6455.4   28.61  6571.7    27.7
#Mann= 3 ,-1 , 0
 4179.46     .12       0  4976.8    .045       0  5053.2     .12       0
#Block Obstruct= 3 ,-1
 4197.37 4679.73    21.3 5928.33 6163.82      27    5700    5850      26
Bank Sta=4976.8,5053.2
XS Rating Curve= 0 ,0
Exp/Cntr=0.5,0.3

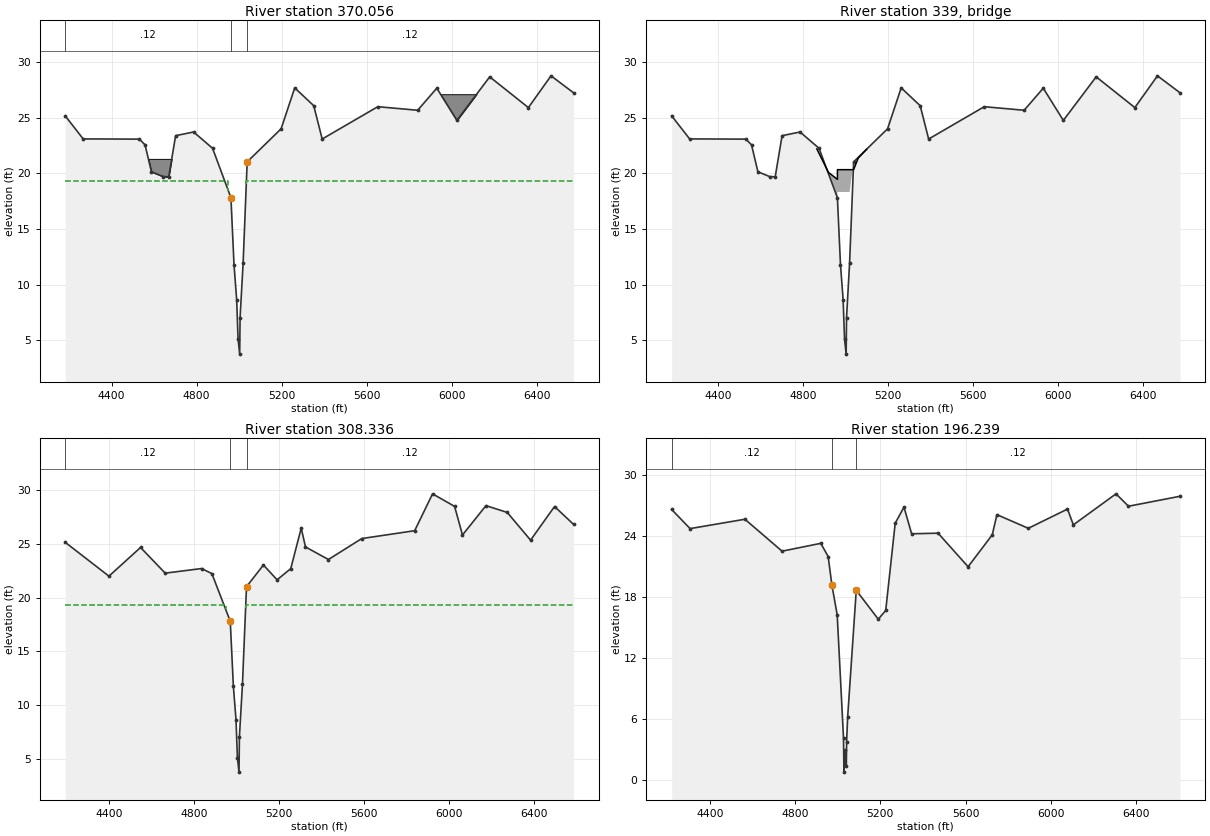
Type RM Length L Ch R = 1 ,370.056 ,60.01,61.72,63.45
BEGIN DESCRIPTION:
access road
END DESCRIPTION:
XS GIS Cut Line= 4
     3179234.534    13770281.181     3178779.549    13770814.847
     3178522.979    13771115.889      3177665.83    13772086.682
#Sta/Elev= 30
 4181.98   25.15 4266.48   23.08 4531.16   23.06 4557.68   22.55  4587.7   20.13
 4642.92    19.7 4669.14   19.68 4701.56   23.37 4786.11    23.7 4875.31   22.24
  4961.8    17.8 4976.36   11.77 4988.79    8.65 4995.37    5.13    5003    3.77
 5004.81    7.05 5019.13   11.93  5038.2   21.02 5197.96   23.99 5261.96   27.66
 5351.36   26.06 5391.16   23.07 5652.84   25.97 5840.44   25.65 5930.48   27.63
 6024.96   24.74 6179.44   28.65 6361.38   25.89 6467.92   28.74 6573.86   27.22
#Mann= 3 ,-1 , 0
 4181.98     .12       0  4961.8    .045       0  5038.2     .12       0
#XS Ineff= 2 , 0
       0    4950    19.3    5034       0    19.3
Permanent Ineff=
       F       F
#Block Obstruct= 2 ,-1
 4556.27 4701.86   21.29 5924.91 6174.06   27.09
Bank Sta=4961.8,5038.2
XS Rating Curve= 0 ,0
Exp/Cntr=0.5,0.3

Type RM Length L Ch R = 3 ,339     ,,,
BEGIN DESCRIPTION:
Bridge at access road
END DESCRIPTION:
Bridge Culvert--1,0,-1,-1, 0
Deck Dist Width WeirC Skew NumUp NumDn MinLoCord MaxHiCord MaxSubmerge Is_Ogee
5,20,2.6,0, 9, 9, , , 0.95, 0, 0,0,,
    4865    4920    4962    4962    4997    5038    5038    5060    5099
   22.18   20.07   19.45   20.32   20.32   20.32   20.32   21.37   22.14
       0       0       0   18.32   18.32   18.32       0       0       0
    4865    4920    4962    4962    4997    5038    5038    5060    5099
   22.18   20.07   19.45   20.32   20.32   20.32   20.32   21.37   22.14
       0       0       0   18.32   18.32   18.32   18.32   18.32       0
BR Coef=-1 , 1 , 0 ,, 0 ,,,0.8,-1,2,0,
WSPro=,,,, 1 ,,,, 0 ,,,, 0 ,,,,-1 ,-1 ,-1 , 0 , 0 , 0 , 0 , 0
BC Design=,, 0 ,, 0 ,,,,,,
BC HTab HWMax=28.74
BC Use User HTab Curves=0
BC User HTab FreeFlow(D)= 0

Type RM Length L Ch R = 1 ,308.336 ,85.27,112.1,134.66
BEGIN DESCRIPTION:
access road
END DESCRIPTION:
XS GIS Cut Line= 4
     3179188.875    13770242.254     3178733.888    13770775.924
     3178477.655     13771076.57     3177620.853    13772046.969
#Sta/Elev= 30
 4195.48   25.15  4401.2      22 4549.82   24.67 4665.84   22.28 4836.69   22.71
 4885.31   22.24  4971.8    17.8 4986.36   11.77 4998.79    8.65 5005.37    5.13
    5013    3.77 5014.81    7.05 5029.13   11.93  5048.2   21.02 5127.85   23.04
    5192   21.66 5256.28    22.7 5305.58   26.47 5325.54   24.72 5433.56   23.55
 5590.36    25.5 5839.14   26.23 5923.34   29.66 6026.96   28.49    6064   25.83
 6174.46   28.56 6274.48   27.93  6384.3   25.35 6497.02   28.48 6586.32   26.82
#Mann= 3 ,-1 , 0
 4195.48     .12       0  4971.8    .045       0  5048.2     .12       0
#XS Ineff= 2 , 0
       0    4950    19.3    5044       0    19.3
Permanent Ineff=
       F       F
Bank Sta=4971.8,5048.2
XS Rating Curve= 0 ,0
Exp/Cntr=0.5,0.3

Type RM Length L Ch R = 1 ,196.239 ,223.43,196.24,214.74
BEGIN DESCRIPTION:
access road
END DESCRIPTION:
XS GIS Cut Line= 4
     3179133.946    13770182.074     3178691.298    13770682.606
     3178442.734     13770937.98     3177530.234    13771946.872
#Sta/Elev= 30
 4221.34   26.63 4307.68   24.75 4564.92   25.67 4739.24   22.53  4920.9    23.3
  4955.6      22 4972.68   19.24 4997.92   16.27 5027.51    4.16 5029.63      .8
 5036.14    2.95 5040.76    1.39 5042.15     3.8 5046.95     6.2 5087.32   18.68
 5190.74   15.84 5225.54    16.7 5270.08   25.28 5311.24   26.86 5347.22   24.24
 5471.32    24.3    5612      21 5725.48   24.14 5747.34   26.12 5894.58   24.78
  6078.4   26.67  6105.9   25.12 6306.06   28.17 6364.56   26.95 6606.22   27.93
#Mann= 3 ,-1 , 0
 4221.34     .12       0 4972.68    .045       0 5087.32     .12       0
Bank Sta=4972.68,5087.32
XS Rating Curve= 0 ,0
Exp/Cntr=0.3,0.1
LCMann Table=0

Chan Stop Cuts=-1
Use User Specified Reach Order=0
Composite Channel Slope=5